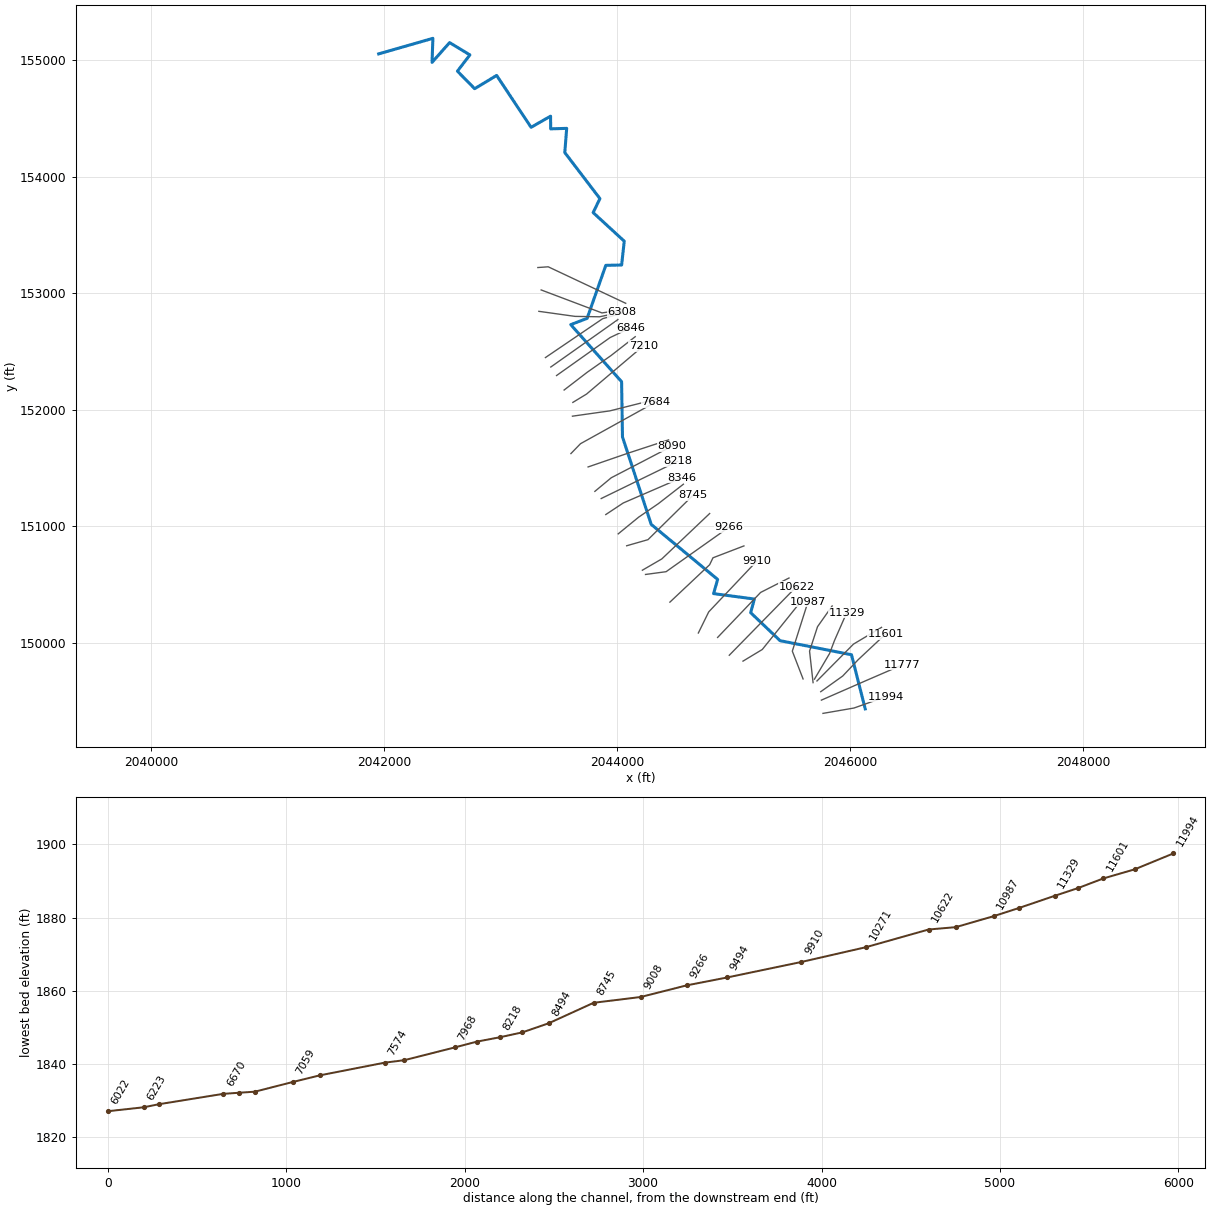
--- CRCKDCK.prj (project) ---

Proj Title=CRCKDCK
Current Plan=p01
Default Exp/Contr=0,0
English Units
Geom File=g01
Flow File=f01
Plan File=p01
Background Map Layer=Inundation Boundary (01pct Value_0)
BEGIN DESCRIPTION:
Stream Name: Crooked Creek
Flood Zone: Approximate
Monroe County, West Virginia
HEC-RAS Version: 5.0.7
Vertical Datum: NAVD88
Projection: NAD 1983 StatePlane West Virginia S FIPS 4702 (US Feet)
LiDAR: 2016, 1-meter
Land Use: 2016 NLCD
Hydrology Method:
Regression.
Model Notes:
END DESCRIPTION:
DSS Export Rating Curves= 0
DSS Export Rating Curve Sorted= 0
DSS Export Volume Flow Curves= 0
DXF OffsetX= 0
DXF OffsetY= 0
DXF ScaleX= 0
DXF ScaleY= 0

--- CRCKDCK.p01 (plan) ---

Plan Title=Floodplain
Program Version=5.07
Short Identifier=Floodplain
Geom File=g01
Flow File=f01
Subcritical Flow
K Sum by GR= 0
Std Step Tol= 0.01
Critical Tol= 0.01
Num of Std Step Trials= 20
Max Error Tol= 0.3
Flow Tol Ratio= 0.001
Split Flow NTrial= 30
Split Flow Tol= 0.02
Split Flow Ratio= 0.02
Log Output Level= 0
Friction Slope Method= 1
Unsteady Friction Slope Method= 2
Unsteady Bridges Friction Slope Method= 1
Parabolic Critical Depth
Global Vel Dist= 0 , 0 , 0
Global Log Level= 0
CheckData=True
Encroach Param=-1 ,0,0, 0
Mapping Interval=1HOUR
Computation Time Step Use Courant=        0
Computation Time Step Use Time Series=    0
Computation Time Step Count To Double=0
Computation Time Step Max Doubling=0
Computation Time Step Max Halving=0
Computation Time Step Residence Courant=0
Run HTab= 0
Run UNet= 0
Run Sediment= 0
Run PostProcess= 0
Run WQNet= 0
Run RASMapper=-1
UNET Theta= 0
UNET Theta Warmup= 0
UNET ZTol= 0
UNET ZSATol= 0
UNET MxIter= 0
UNET Max Iter WO Improvement= 0
UNET MaxInSteps= 0
UNET DtIC= 0
UNET DtMin= 0
UNET MaxCRTS= 0
UNET WFStab= 0
UNET SFStab= 0
UNET WFX= 1
UNET SFX= 1
UNET 1D Methodology=Finite Difference
UNET DSS MLevel= 1
UNET Pardiso=0
UNET DZMax Abort= 0
UNET Use Existing IB Tables= 0
UNET Froude Reduction=False
UNET Froude Limit= 0
UNET Froude Power= 0
UNET D1 Cores= 0
UNET D2 Coriolis=0
UNET D2 Cores= 0
UNET D2 Theta= 1
UNET D2 Theta Warmup= 1
UNET D2 Z Tol= 0.01
UNET D2 Volume Tol= 0.01
UNET D2 Max Iterations= 20
UNET D2 Equation= 0
UNET D2 RampUpFraction=0.1
UNET D2 TimeSlices= 1
UNET D2 BCVolumeCheck=0
UNET D1D2 MaxIter= 0
UNET D1D2 ZTol=0.01
UNET D1D2 QTol=0.1
UNET D1D2 MinQTol=1
Write IC File= 0
Write IC File at Fixed DateTime=0
Write IC File at Sim End=0
Echo Input=False
Echo Parameters=False
Echo Output=False
Write Detailed= 0
HDF Write Warmup=0
HDF Write Time Slices=0
HDF Flush=0
HDF Face Node Velocities=0
HDF Compression= 1
HDF Chunk Size= 1
HDF Spatial Parts= 1
HDF Use Max Rows=0
HDF Fixed Rows= 1
Calibration Method= 0
Calibration Iterations= 20
Calibration Max Change=0.05
Calibration Tolerance=0.2
Calibration Maximum=1.5
Calibration Minimum=0.5
Calibration Optimization Method= 1
WQ AD Non Conservative
WQ ULTIMATE=-1
WQ Max Comp Step=1HOUR
WQ Output Interval=15MIN
WQ Output Selected Increments= 0
WQ Output face flow=0
WQ Output face velocity=0
WQ Output face area=0
WQ Output face dispersion=0
WQ Output cell volume=0
WQ Output cell surface area=0
WQ Output cell continuity=0
WQ Output cumulative cell continuity=0
WQ Output face conc=0
WQ Output face dconc_dx=0
WQ Output face courant=0
WQ Output face peclet=0
WQ Output face adv mass=0
WQ Output face disp mass=0
WQ Output cell mass=0
WQ Output cell source sink temp=0
WQ Output nsm pathways=0
WQ Output nsm derived pathways=0
WQ Output MaxMinRange=-1
WQ Daily Max Min Mean=-1
WQ Daily Range=0
WQ Daily Time=0
WQ Create Restart=0
WQ Fixed Restart=0
WQ System Summary=0
WQ Write To DSS=0
WQ Use Fixed Temperature=0
Sorting and Armoring Iterations= 10
XS Update Threshold= 0.02
Bed Roughness Predictor= 0
Hydraulics Update Threshold= 0.02
Energy Slope Method= 1
Volume Change Method= 1
Sediment Retention Method= 0
XS Weighting Method= 0
Number of US Weighted Cross Sections= 1
Number of DS Weighted Cross Sections= 1
Upstream XS Weight=0
Main XS Weight=1
Downstream XS Weight=0
Number of DS XS's Weighted with US Boundary= 1
Upstream Boundary Weight= 1
Weight of XSs Associated with US Boundary= 0
Number of US XS's Weighted with DS Boundary= 1
Downstream Boundary Weight= 0.5
Weight of XSs Associated with DS Boundary= 0.5
Percentile Method= 0
Sediment Output Level= 3
Mass or Volume Output= 0
Output Increment Type= 1
Profile and TS Output Increment= 1
XS Output Flag= 0
XS Output Increment= 10
Write Gradation File= 0
Read Gradation Hotstart= 0
Write HDF5 File= 1
Write Binary Output= 1
Write DSS Sediment File= 0
SV Curve= 0
Specific Gage Flag= 0

--- CRCKDCK.f01 (steady flow) ---

Flow Title=Flow
Program Version=5.07
Number of Profiles= 6
Profile Names=01pct,10pct,04pct,02pct,0_2pct,01plus
River Rch & RM=CRCKDCK,Main            ,11994
     747     399     528     634    1040    1100
River Rch & RM=CRCKDCK,Main            ,11777
     754     403     533     640    1050    1120
River Rch & RM=CRCKDCK,Main            ,10775
     975     526     692     829    1350    1440
River Rch & RM=CRCKDCK,Main            ,7684
    1080     586     770     921    1490    1600
River Rch & RM=CRCKDCK,Main            ,5643
    1190     646     847    1010    1640    1760
River Rch & RM=CRCKDCK,Main            ,5175
    1230     668     876    1050    1690    1810
Boundary for River Rch & Prof#=CRCKDCK,Main            , 1
Up Type= 0
Dn Type= 3
Dn Slope=0.00638
Boundary for River Rch & Prof#=CRCKDCK,Main            , 2
Up Type= 0
Dn Type= 3
Dn Slope=0.00638
Boundary for River Rch & Prof#=CRCKDCK,Main            , 3
Up Type= 0
Dn Type= 3
Dn Slope=0.00638
Boundary for River Rch & Prof#=CRCKDCK,Main            , 4
Up Type= 0
Dn Type= 3
Dn Slope=0.00638
Boundary for River Rch & Prof#=CRCKDCK,Main            , 5
Up Type= 0
Dn Type= 3
Dn Slope=0.00638
Boundary for River Rch & Prof#=CRCKDCK,Main            , 6
Up Type= 0
Dn Type= 3
Dn Slope=0.00638
DSS Import GetInterval= 0
DSS Import GetPeak= 0
DSS Import FillOption= 0

--- CRCKDCK.g01 (geometry) ---

Geom Title=Geometry
Program Version=5.07

River Reach=CRCKDCK         ,Main
Reach XY= 30
     2046127.949      149433.304     2046009.946      149898.204
     2045397.156      150019.037     2045144.986      150259.315
     2045176.844      150376.502     2044826.844      150422.943
     2044861.566      150544.905     2044291.688      151017.388
      2044045.16      151768.082     2044037.521      152242.388
2043601.37461029152732.187827291     2043741.688      152786.138
     2043902.104      153241.173      2044037.81      153244.153
      2044060.38       153448.58     2043793.453       153694.24
     2043851.613       153814.06     2043550.154      154209.547
     2043566.474      154417.185     2043428.974      154413.019
     2043428.279      154522.046     2043260.918      154426.213
     2042965.432      154871.699      2042776.89       154757.81
     2042628.974      154908.157     2042735.918      155047.741
      2042561.96      155153.644     2042411.265      154983.852
     2042418.557      155190.102      2041953.43      155056.663

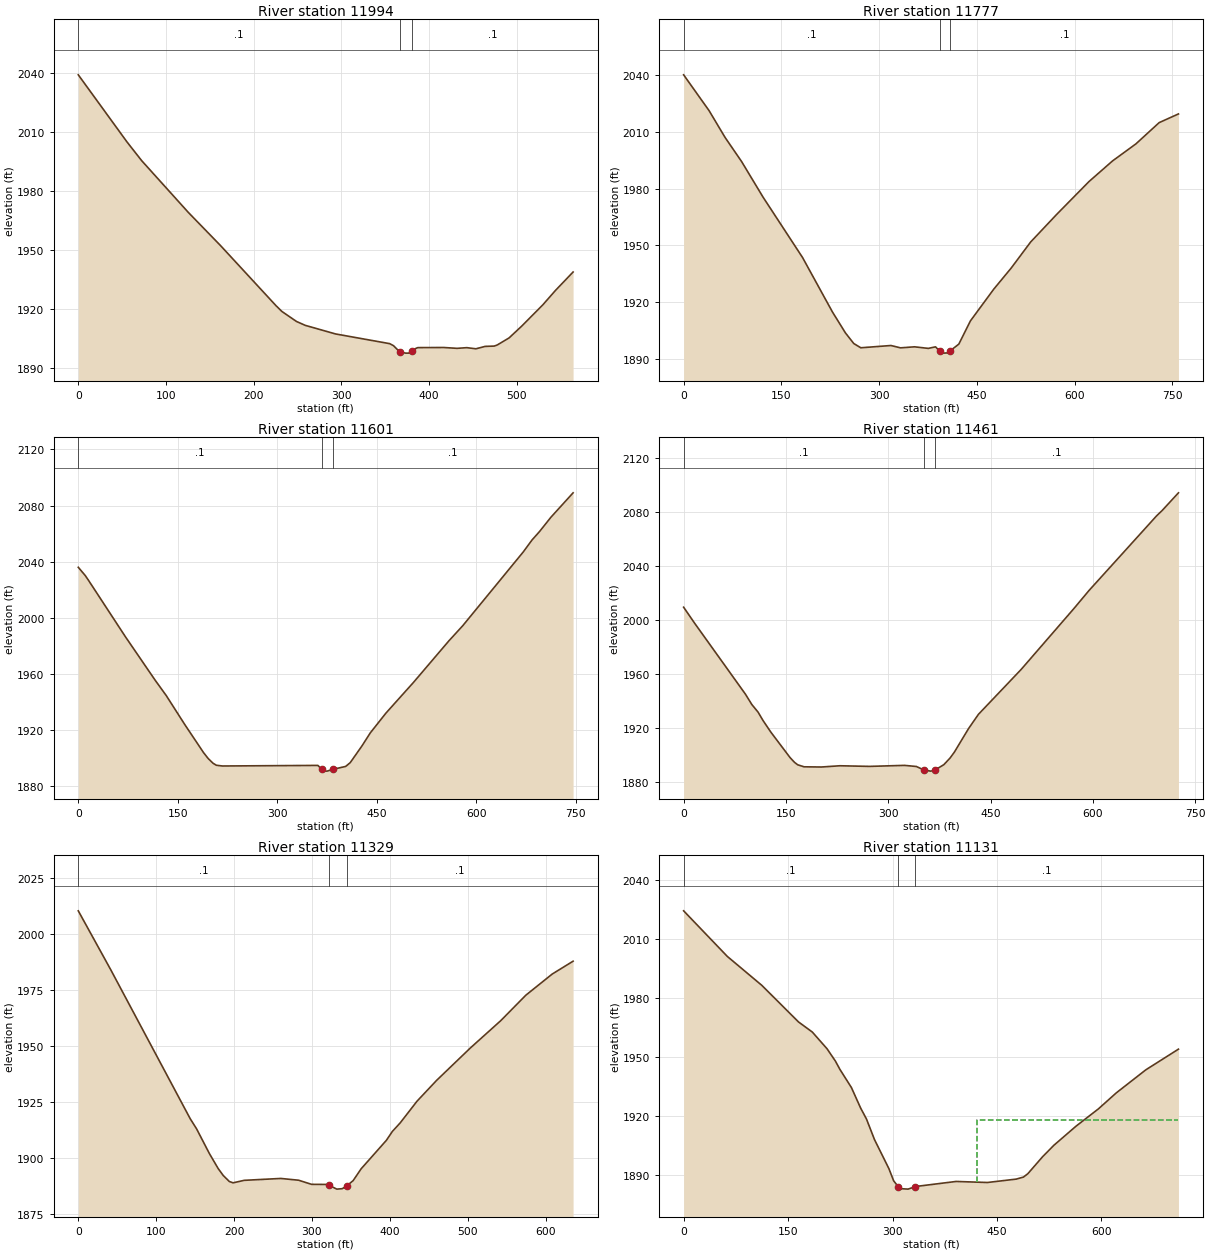
Type RM Length L Ch R = 1 ,11994   ,213.5,217.5,216.2
XS GIS Cut Line= 3
     2045765.421      149394.839     2046031.862      149440.864
     2046308.557      149539.456
#Sta/Elev= 30
       0    2039    55.7 2004.79    72.4 1995.31   125.6    1969   162.3 1952.15
   225.5 1921.63   232.2  1918.7   248.8 1913.63   258.8 1911.66   293.3  1907.3
     355 1902.37   359.3 1901.35  366.211898.288   373.2 1897.55   376.7 1897.56
   380.11898.416   383.7 1899.73   387.1 1900.35   416.6 1900.41     432 1899.98
   442.9 1900.33   453.3 1899.75   463.8 1900.97   474.2 1901.13   477.7 1901.71
   491.1 1905.27   505.6 1911.31   529.6  1922.1   543.9 1929.36   564.1 1938.78
#Mann= 3 ,-1 , 0
       0      .1       0  366.21    .045       0   380.1      .1       0
Bank Sta=366.21,380.1
XS Rating Curve= 0 ,0
Exp/Cntr=0.3,0.1

Type RM Length L Ch R = 1 ,11777   ,170.5,175.7,181.1
XS GIS Cut Line= 3
     2045751.692       149508.56     2046118.904      149669.291
     2046447.905      149811.679
#Sta/Elev= 30
       0 2039.97    39.1 2021.05    63.6 2006.94    88.9 1994.26   121.9 1975.44
   182.4 1943.66   228.4 1914.87   248.3 1903.85   261.1 1898.24   271.9 1896.01
   318.1 1897.21   332.8 1895.97   354.3 1896.52   375.4 1895.69   386.5 1896.51
  392.811894.326   397.8 1893.19   404.4 1893.29  408.931894.375   422.3 1897.95
   440.1  1910.2   475.9 1926.93   502.6 1938.04   532.5  1951.8   572.4 1966.34
   622.1  1983.7   658.2 1994.57     694 2003.54   729.7 2014.76   759.3 2019.34
#Mann= 3 ,-1 , 0
       0      .1       0  392.81    .045       0  408.93      .1       0
Bank Sta=392.81,408.93
XS Rating Curve= 0 ,0
Exp/Cntr=0.3,0.1

Type RM Length L Ch R = 1 ,11601   ,139.7,140.3,138.5
XS GIS Cut Line= 4
2045746.11487654149580.8434202662045934.61391316149715.485589281
2046069.25608218149857.4718766062046301.81982866150075.347386465
#Sta/Elev= 30
       0 2036.01    10.6 2030.07    15.5 2026.66      71 1986.54   116.1 1955.38
   132.6 1944.58   160.8 1923.74     189  1903.8   195.8 1899.71   203.1 1896.35
   208.1  1894.9   217.2 1894.36   361.2 1894.78   367.11892.047   370.5 1890.79
   375.2  1890.7   383.51891.942   403.1 1894.05     410 1896.75   427.9 1908.82
   440.2 1917.93   463.8 1932.04   505.2 1953.86   558.9 1983.65   579.5 1994.28
   670.7 2046.85   684.1 2055.48   695.5 2061.54   712.5 2071.65     746 2089.09
#Mann= 3 ,-1 , 0
       0      .1       0   367.1    .045       0   383.5      .1       0
Bank Sta=367.1,383.5
XS Rating Curve= 0 ,0
Exp/Cntr(USF)=0,0
Exp/Cntr=0.3,0.1

Type RM Length L Ch R = 1 ,11461   ,126.5,131.5,136.5
XS GIS Cut Line= 3
     2045713.822      149673.033     2046027.091      149989.484
     2046267.765      150133.235
#Sta/Elev= 30
       0 2009.48    16.1 1997.64    90.7 1945.03    99.9  1937.5   109.2 1931.75
   116.2 1925.76   127.8 1917.03     156 1898.16   162.6 1894.59   167.3 1892.78
   176.6 1891.29   202.1 1891.14   229.2 1892.06   272.6  1891.6   323.9 1892.35
   341.3 1891.52  352.471888.931   362.2 1888.09  368.571888.892   381.5 1892.85
   390.8 1897.85     397 1902.15   417.8 1919.59   432.3 1930.15   494.9 1963.37
   572.5  2008.6   594.2 2021.71   693.6 2077.17   701.7 2081.09   725.6 2094.19
#Mann= 3 ,-1 , 0
       0      .1       0  352.47    .045       0  368.57      .1       0
Bank Sta=352.47,368.57
XS Rating Curve= 0 ,0
Exp/Cntr=0.3,0.1

Type RM Length L Ch R = 1 ,11329   ,196.8,198.5,197.5
XS GIS Cut Line= 4
2045692.25800894149688.5571554782045822.00409908149908.880704775
 2045863.6207695150019.0424794232045968.88646527150258.950344213
#Sta/Elev= 30
       0 2010.32    41.6 1984.05   143.7 1917.44     152 1912.85   168.3  1901.9
   179.6 1895.18   186.2 1892.03     194 1889.36   198.8 1888.78   213.1 1889.89
   260.2 1890.73   282.9 1889.94   299.6  1888.1     318 1888.06   322.5 1887.61
     332 1885.96     339 1886.16   345.4 1887.58     353 1889.78   363.2 1895.03
   395.6 1907.75   403.3 1911.73   413.3 1915.52     435 1925.26   460.1 1934.54
   503.5 1949.04   542.5 1961.24   574.7 1972.61   608.6 1982.07   635.4 1987.81
#Mann= 3 ,-1 , 0
       0      .1       0   322.5    .045       0   345.4      .1       0
Bank Sta=322.5,345.4
XS Rating Curve= 0 ,0
Exp/Cntr(USF)=0,0
Exp/Cntr=0.3,0.1

Type RM Length L Ch R = 1 ,11131   ,142.7,143.8,144.8
XS GIS Cut Line= 4
     2045680.428      149658.722     2045650.214      149929.056
     2045718.592      150138.962     2045844.218      150317.065
#Sta/Elev= 30
       0 2024.53    62.7  2001.3   112.3 1986.54   165.1 1967.86   184.9 1962.71
     206  1954.2     218 1947.92   224.5 1943.68     241 1934.43   254.2 1924.01
   262.6 1918.41   274.1 1907.94   294.8 1893.12   301.7 1886.88  308.22 1883.89
   312.1 1882.89   322.4 1882.66  332.921883.984   391.4 1886.57   436.3 1886.04
   477.7 1887.77   488.1 1888.81   494.3 1890.49   515.6 1899.18   531.9 1905.05
   563.6 1914.75   595.7 1923.56   621.4 1931.72   663.9 1943.49   710.7 1954.01
#Mann= 3 ,-1 , 0
       0      .1       0  308.22    .045       0  332.92      .1       0
#XS Ineff= 2 , 0
                          421.17         1917.92
Permanent Ineff=
       F       F
Bank Sta=308.22,332.92
XS Rating Curve= 0 ,0
Exp/Cntr=0.3,0.1

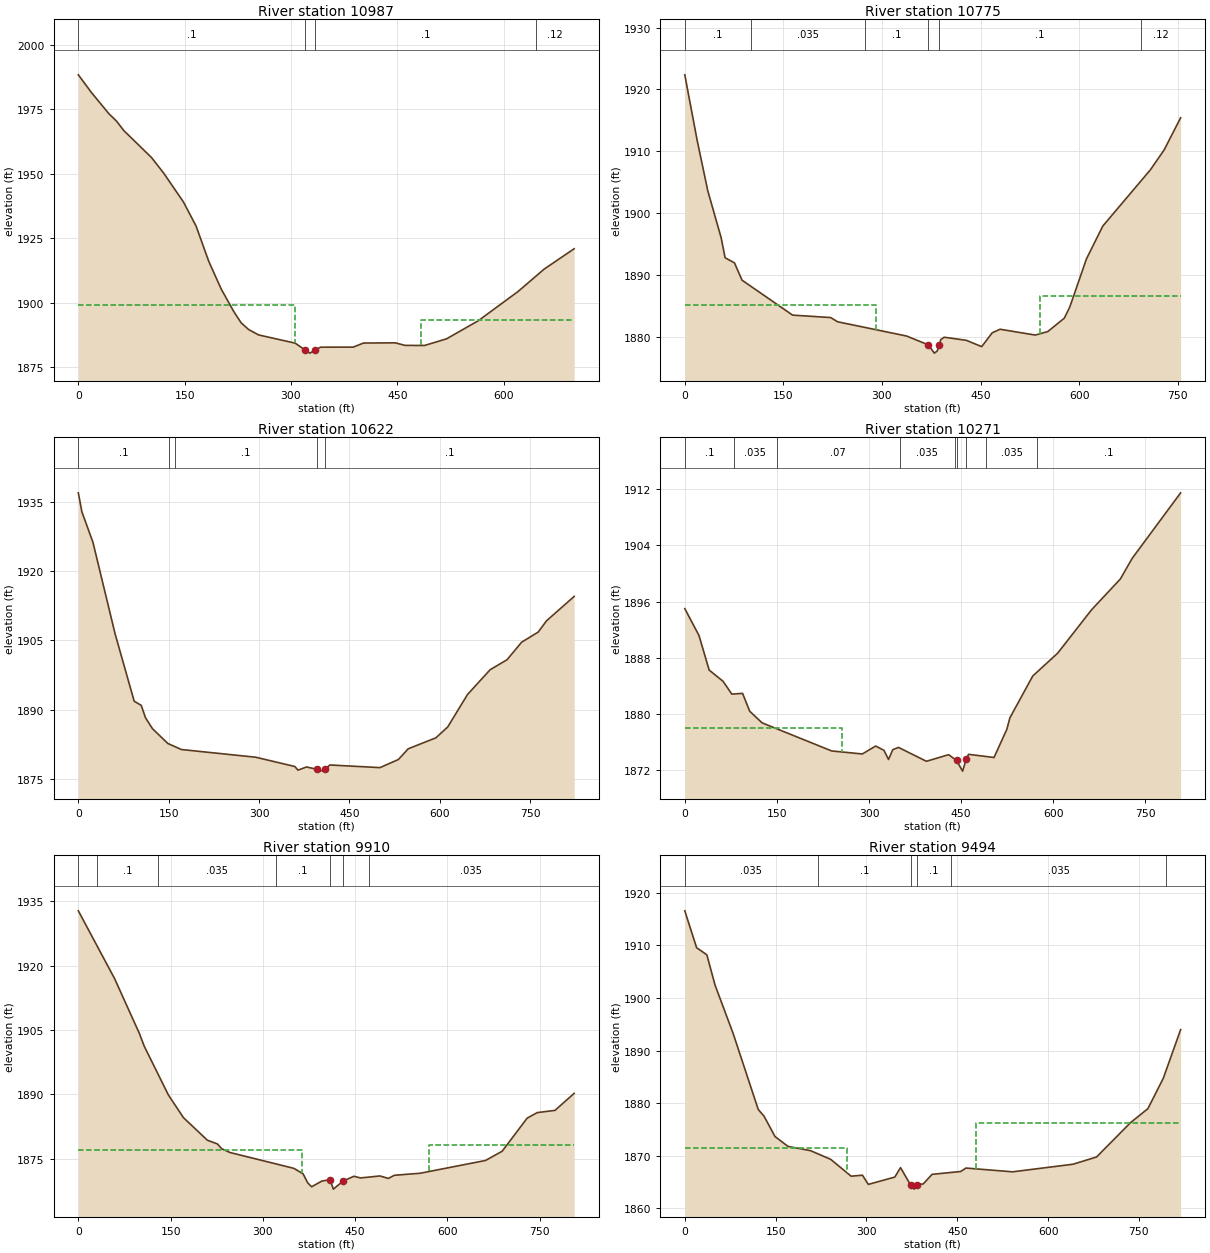
Type RM Length L Ch R = 1 ,10987   ,215.6,212,207.6
XS GIS Cut Line= 3
     2045594.557      149690.526     2045502.325      149929.056
     2045636.603      150352.025
#Sta/Elev= 30
       0 1988.26    18.7 1981.33    43.3 1973.13    53.9 1970.32    64.4 1966.59
   103.1 1956.24   120.5 1950.14   148.4 1938.92   166.2 1929.59     184 1915.97
   201.8  1905.1   219.4 1896.47   229.7 1892.13   240.3 1889.53   254.4 1887.44
     306 1884.25  320.091881.561   326.7 1880.39  333.911881.555   341.7 1882.69
   387.8 1882.72   402.4  1884.3   447.2 1884.38   460.9 1883.39   488.5 1883.36
   519.4 1885.92   564.2 1892.93   620.3 1904.26   657.1 1912.94   699.5 1920.85
#Mann= 4 ,-1 , 0
       0      .1       0  320.09    .045       0  333.91      .1       0
  645.74     .12       0
#XS Ineff= 2 , 0
          305.98 1899.09  482.88         1893.22
Permanent Ineff=
       F       F
Bank Sta=320.09,333.91
XS Rating Curve= 0 ,0
Exp/Cntr=0.3,0.1

Type RM Length L Ch R = 1 ,10775   ,153.5,152.9,151.7
XS GIS Cut Line= 3
      2045079.11      149843.359     2045244.712      149943.368
     2045596.147      150380.673
#Sta/Elev= 30
       0 1922.37    18.9 1911.73      35 1903.62    55.4 1896.01    61.3 1892.81
    75.6 1891.98    87.1 1889.18   164.1 1883.53     222 1883.14   232.4 1882.46
   337.6 1880.15   370.61878.723   379.7 1877.39   384.1 1877.72     3871878.695
   389.6 1879.58   394.8 1879.96   428.4 1879.46   451.8 1878.44   467.8 1880.68
   479.8 1881.25   533.4 1880.31   552.3 1880.87   577.5 1883.04   585.9 1884.86
   611.2 1892.62   636.1 1897.93   708.5 1907.02   729.5 1910.25   754.5 1915.43
#Mann= 6 ,-1 , 0
       0      .1       0     100    .035       0  273.46      .1       0
   370.6    .045       0     387      .1       0  693.46     .12       0
#XS Ineff= 2 , 0
          291.53  1885.2  541.02         1886.68
Permanent Ineff=
       F       F
Bank Sta=370.6,387
XS Rating Curve= 0 ,0
Exp/Cntr=0.3,0.1

Type RM Length L Ch R = 1 ,10622   ,333.7,350.7,347.7
XS GIS Cut Line= 2
2044961.48979358 149894.032254052045537.36279358 150482.27925405
#Sta/Elev= 30
       0 1936.92     5.9 1932.82    24.3 1926.21      61 1906.45    92.7 1891.87
   104.5 1890.95   111.5 1888.29   123.1 1885.92   148.6 1882.72   171.2 1881.41
   294.4 1879.75   359.4 1877.74   364.7 1876.95   378.8 1877.64   396.2 1877.14
   401.5 1876.74   409.9 1877.23   417.7 1878.07   500.8  1877.5   531.4 1879.25
   547.7 1881.57   593.6 1883.94   613.3 1886.29   646.1  1893.3   683.7 1898.67
   711.8 1900.83   735.9 1904.61   763.5 1906.81   777.3 1909.24   823.2 1914.52
#Mann= 5 ,-1 , 0
       0      .1       0     150    .035       0     160      .1       0
   396.2    .045       0   409.9      .1       0
Bank Sta=396.2,409.9
XS Rating Curve= 0 ,0
Exp/Cntr=0.3,0.1

Type RM Length L Ch R = 1 ,10271   ,350.8,361.6,355.1
XS GIS Cut Line= 3
     2044861.474      150046.731       2045230.4       150433.15
     2045473.965      150557.061
#Sta/Elev= 30
       0 1895.02    23.2 1891.18    39.7 1886.28    62.3 1884.69    76.6 1882.86
    94.1 1882.97   105.7 1880.43   125.8 1878.78   239.2 1874.78   289.1 1874.35
   310.9 1875.48   324.3 1874.87   331.8 1873.57   338.8 1874.97   348.1 1875.28
   393.5 1873.31   429.7 1874.25   442.51873.427   452.4 1871.91  458.131873.564
   462.1  1874.3   503.6 1873.85   524.4 1877.84   529.5  1879.5   566.7 1885.44
   607.2 1888.68   662.4 1894.85   709.4 1899.24   728.6 1902.17   807.5 1911.49
#Mann= 9 ,-1 , 0
       0      .1       0      80    .035       0     150     .07       0
     350    .035       0     440      .1       0   442.5    .045       0
  458.13      .1       0     490    .035       0  574.25      .1       0
#XS Ineff= 2 , 0
          255.93 1877.98
Permanent Ineff=
       F       F
Bank Sta=442.5,458.13
XS Rating Curve= 0 ,0
Exp/Cntr=0.3,0.1

Type RM Length L Ch R = 1 ,9910    ,412.2,415.2,410.1
XS GIS Cut Line= 3
     2044696.093      150084.896     2044785.144      150266.179
     2045200.187      150705.074
#Sta/Elev= 30
       0 1932.76    58.9 1916.97    99.1 1904.22   107.3 1901.14   146.5  1889.8
     171 1884.52   209.8 1879.27   226.1 1878.41   233.1 1877.29   246.5 1876.41
   350.3 1872.72   365.3 1871.45   372.9 1869.34   379.2 1868.42   395.6 1869.73
     409 1870.09   414.6 1867.87   430.3 1869.75     448 1870.87   458.7 1870.48
   490.3 1870.94   503.9 1870.37   513.8  1871.1   555.6 1871.57   661.9 1874.55
     689 1876.71   729.6 1884.42   745.9 1885.71   774.8 1886.23     806  1890.2
#Mann= 7 ,-1 , 0
       0    .035       0      30      .1       0     130    .035       0
  321.97      .1       0     409    .045       0   430.3      .1       0
  471.97    .035       0
#XS Ineff= 2 , 0
          363.33  1876.9  570.45         1878.05
Permanent Ineff=
       F       F
Bank Sta=409,430.3
XS Rating Curve= 0 ,0
Exp/Cntr=0.3,0.1

Type RM Length L Ch R = 1 ,9494    ,226,228.7,225.1
XS GIS Cut Line= 4
2044451.98768084150349.876198596 2044793.0956206150671.121865266
 2044821.5164433150730.4348865712045087.13086524150832.462751775
#Sta/Elev= 30
       0 1916.57    19.5 1909.56    36.4 1908.21    49.9 1902.47    79.9 1893.22
   121.3 1878.79   130.8 1877.53     149 1873.64   170.4 1871.77   207.6 1870.96
   240.9 1869.31   274.8  1866.1   293.4 1866.29   303.1 1864.54   346.8 1865.93
   356.3 1867.73   372.91864.434   378.9 1863.64   383.9  1864.4     394 1864.65
   408.4 1866.45   455.5 1866.99   464.5 1867.65   541.4 1866.93   641.3 1868.38
     680 1869.75   736.2 1876.29   764.9 1878.95   790.3 1884.73   818.9 1893.97
#Mann= 6 ,-1 , 0
       0    .035       0     220      .1       0   372.9    .045       0
   383.9      .1       0     440    .035       0  794.34      .1       0
#XS Ineff= 2 , 0
          268.17 1871.53   481.1         1876.17
Permanent Ineff=
       F       F
Bank Sta=372.9,383.9
XS Rating Curve= 0 ,0
Exp/Cntr=0.3,0.1

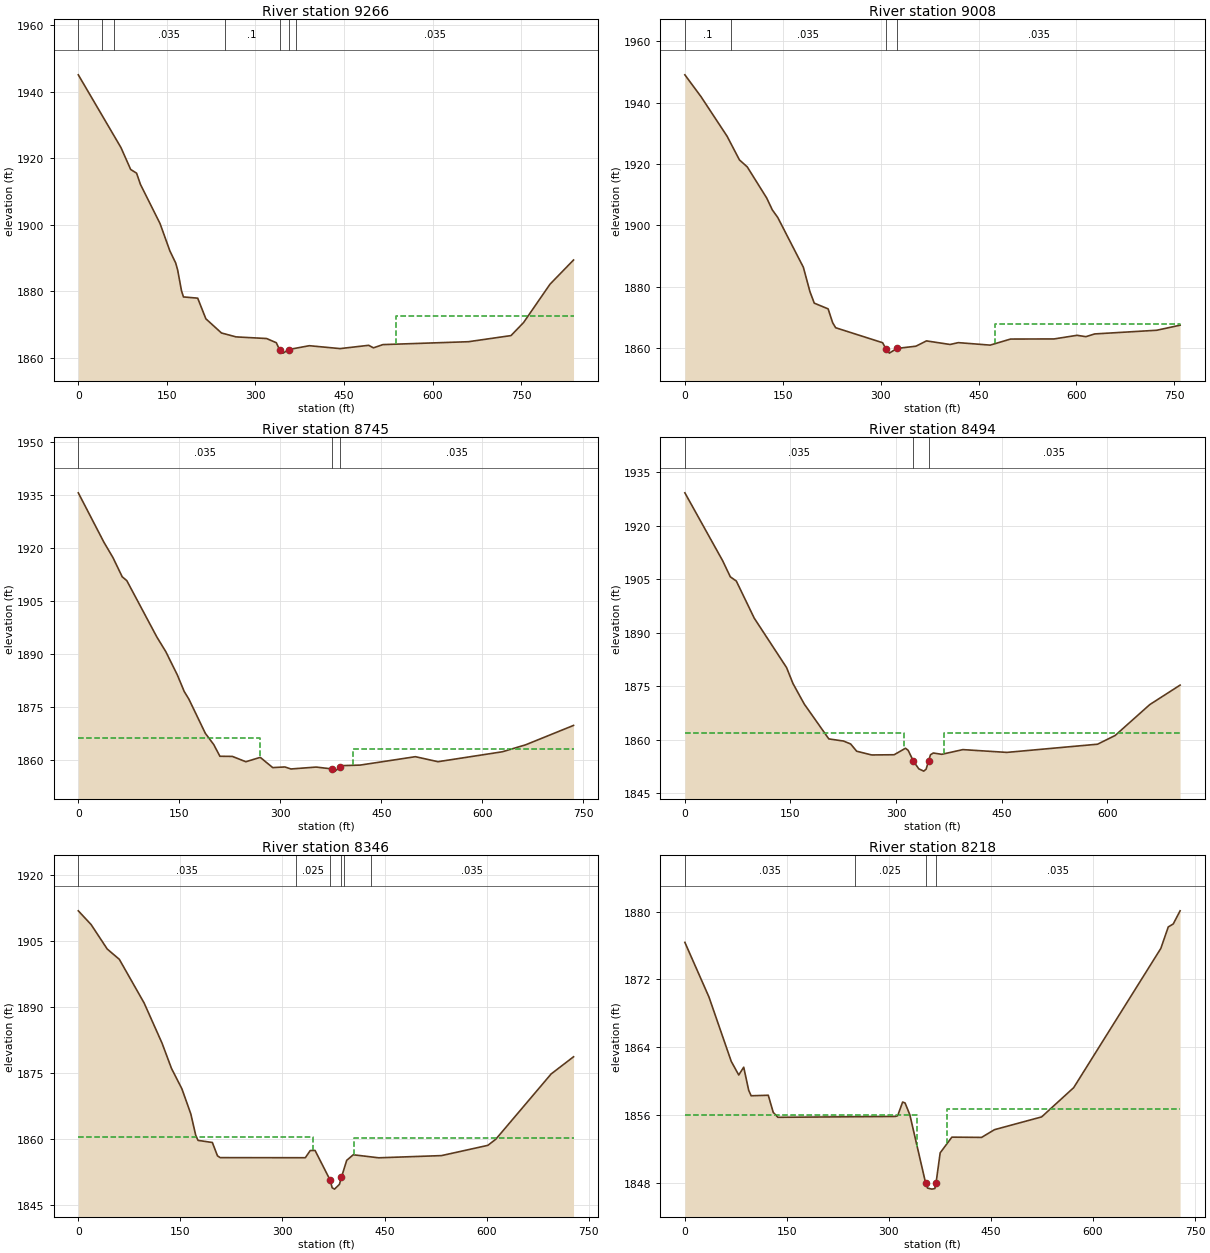
Type RM Length L Ch R = 1 ,9266    ,250.8,257.7,254.8
XS GIS Cut Line= 3
     2044242.885      150587.399     2044419.398      150611.252
     2044958.476      150992.901
#Sta/Elev= 30
       0 1945.11    72.2 1923.26    88.7 1916.66    98.7 1915.55   105.3 1912.15
   138.4 1900.41     155 1892.22   164.9 1888.55   168.2 1886.48   174.8 1880.17
   178.1 1878.35   202.2 1877.98     216 1871.78   242.4 1867.52   267.1 1866.34
   318.8 1865.85   335.3 1864.59  340.831862.482   346.8 1861.46  356.331862.543
   391.2 1863.69   443.3 1862.82   491.7 1863.81   499.8 1863.05   515.8 1864.02
   660.5 1864.89   732.7 1866.73     754 1870.65   798.7 1882.16   838.6 1889.45
#Mann= 7 ,-1 , 0
       0     .04       0      40      .1       0      60    .035       0
  248.12      .1       0  340.83    .045       0  356.33      .1       0
  368.12    .035       0
#XS Ineff= 2 , 0
                          538.14          1872.5
Permanent Ineff=
       F       F
Bank Sta=340.83,356.33
XS Rating Curve= 0 ,0
Exp/Cntr=0.3,0.1

Type RM Length L Ch R = 1 ,9008    ,259.4,263,258.1
XS GIS Cut Line= 3
     2044215.852      150623.974     2044382.823      150720.976
     2044793.095      151110.576
#Sta/Elev= 30
       0 1949.05    24.8 1941.91    64.7 1929.02    83.6 1921.31    95.6 1919.02
   125.4 1908.87     134 1905.01   142.4  1902.5   181.6 1886.27   191.6 1878.37
   198.3 1874.58   219.5 1872.72   226.5 1868.19   231.1 1866.56   303.1 1861.67
  307.851859.725   313.3 1858.28  325.041859.814   354.1 1860.54   370.2 1862.27
   406.4  1861.1   419.1  1861.7   467.8 1860.89   499.1 1862.87   565.8 1862.91
     601 1864.09   614.6 1863.65     628 1864.54   723.1 1865.74   758.9 1867.39
#Mann= 4 ,-1 , 0
       0      .1       0      70    .035       0  307.85    .045       0
  325.04    .035       0
#XS Ineff= 2 , 0
                          475.94         1867.89
Permanent Ineff=
       F       F
Bank Sta=307.85,325.04
XS Rating Curve= 0 ,0
Exp/Cntr=0.3,0.1

Type RM Length L Ch R = 1 ,8745    ,249.9,251.2,245.7
XS GIS Cut Line= 3
 2044081.1540458  150833.7246514 2044264.0270458  150886.2006514
 2044652.1380458  151268.9756514
#Sta/Elev= 30
       0 1935.55    37.9  1921.6    51.5 1917.19    65.2 1911.77      72 1910.68
   116.6 1894.72   129.9 1890.57   147.1 1883.95   157.3 1879.27   164.2 1877.11
   188.7  1867.4   201.1 1864.24   210.3 1860.92   228.8 1860.88   248.8 1859.37
   270.2 1860.61   288.7 1857.71   306.8 1857.89   315.8 1857.32   353.2 1857.86
   376.4 1857.34   381.2 1856.71     388 1857.76   390.6 1858.26   418.6 1858.42
   500.6  1860.8   534.1 1859.38   629.7 1862.19   664.1 1864.15   735.4 1869.66
#Mann= 3 ,-1 , 0
       0    .035       0   376.4    .045       0     388    .035       0
#XS Ineff= 2 , 0
          269.83 1865.99  408.02         1863.06
Permanent Ineff=
       F       F
Bank Sta=376.4,388
XS Rating Curve= 0 ,0
Exp/Cntr=0.3,0.1

Type RM Length L Ch R = 1 ,8494    ,151,148.2,143.1
XS GIS Cut Line= 4
2044008.52436639150935.8719751042044183.02061743151078.641635048
2044353.55104459151195.633439725 2044567.7055345151362.198042993
#Sta/Elev= 30
       0 1929.26    53.6 1910.22    64.6 1905.67    73.1 1904.49    98.5 1894.09
   144.5 1880.19   153.6 1875.71   169.6 1869.96   204.5 1860.17   225.5 1859.56
   235.5 1858.75   244.1 1856.71   265.4 1855.66   297.3 1855.72   313.4 1857.54
   317.2 1856.97   324.8  1853.9   332.3 1851.77   339.4 1851.12   342.7 1851.65
   346.4 1854.06     349 1855.73     353 1856.21   364.9 1855.84   394.9 1857.16
   457.5 1856.38   586.4 1858.68   611.4 1861.14   660.5  1869.8   703.6 1875.27
#Mann= 3 ,-1 , 0
       0    .035       0   324.8    .045       0   346.4    .035       0
#XS Ineff= 2 , 0
          311.75 1861.96  367.91         1861.96
Permanent Ineff=
       F       F
Bank Sta=324.8,346.4
XS Rating Curve= 0 ,0
Exp/Cntr(USF)=0,0
Exp/Cntr=0.3,0.1

Type RM Length L Ch R = 1 ,8346    ,125.8,127.1,127.9
XS GIS Cut Line= 3
     2043902.039      151101.795     2044052.061      151201.217
     2044554.565      151419.075
#Sta/Elev= 30
       0 1911.88    18.8 1908.76    42.5  1903.2    60.3 1900.85    96.7 1890.94
     123 1881.82   136.9 1876.07   152.3  1871.4   165.4 1865.68   172.5 1860.89
   175.9  1859.7     197 1859.22   204.5 1856.19   208.5 1855.78   333.6 1855.76
   340.8 1857.39   347.9 1857.41   370.1 1850.66     373 1848.94   376.5 1848.62
   383.7  1849.7   386.6 1851.29   394.4 1855.16     404 1856.43   441.4 1855.74
   533.7 1856.24   601.8 1858.57   613.6 1859.98   694.8  1874.8   727.7  1878.7
#Mann= 6 ,-1 , 0
       0    .035       0  319.98    .025       0   370.1    .045       0
   386.6    .025       0  389.98     .05       0  429.98    .035       0
#XS Ineff= 2 , 0
          344.99 1860.39  405.73         1860.24
Permanent Ineff=
       F       F
Bank Sta=370.1,386.6
XS Rating Curve= 0 ,0
Exp/Cntr=0.3,0.1

Type RM Length L Ch R = 1 ,8218    ,127.9,128.4,129.2
XS GIS Cut Line= 3
     2043862.656       151239.28     2044189.861      151398.758
     2044517.065      151558.236
#Sta/Elev= 30
       0 1876.37    35.4 1869.93    68.2 1862.33    79.2 1860.73    86.5 1861.65
    93.8 1858.93    97.4 1858.28   122.6 1858.34   129.9 1856.32   136.7 1855.74
   309.3 1855.84   312.8 1855.92   320.1 1857.54   323.7 1857.43   330.7 1856.04
   353.8 1848.03   356.6  1847.4     363 1847.27   367.5 1847.34   369.3 1848.04
   375.3 1851.55   392.5  1853.4   436.2 1853.37   455.1 1854.28   524.5 1855.79
   571.6 1859.24   699.7 1875.66   710.6 1878.19   717.9 1878.54     728 1880.09
#Mann= 4 ,-1 , 0
       0    .035       0     250    .025       0   353.8    .045       0
   369.3    .035       0
#XS Ineff= 2 , 0
          341.55 1855.98   385.1         1856.69
Permanent Ineff=
       F       F
Bank Sta=353.8,369.3
XS Rating Curve= 0 ,0
Exp/Cntr=0.3,0.1

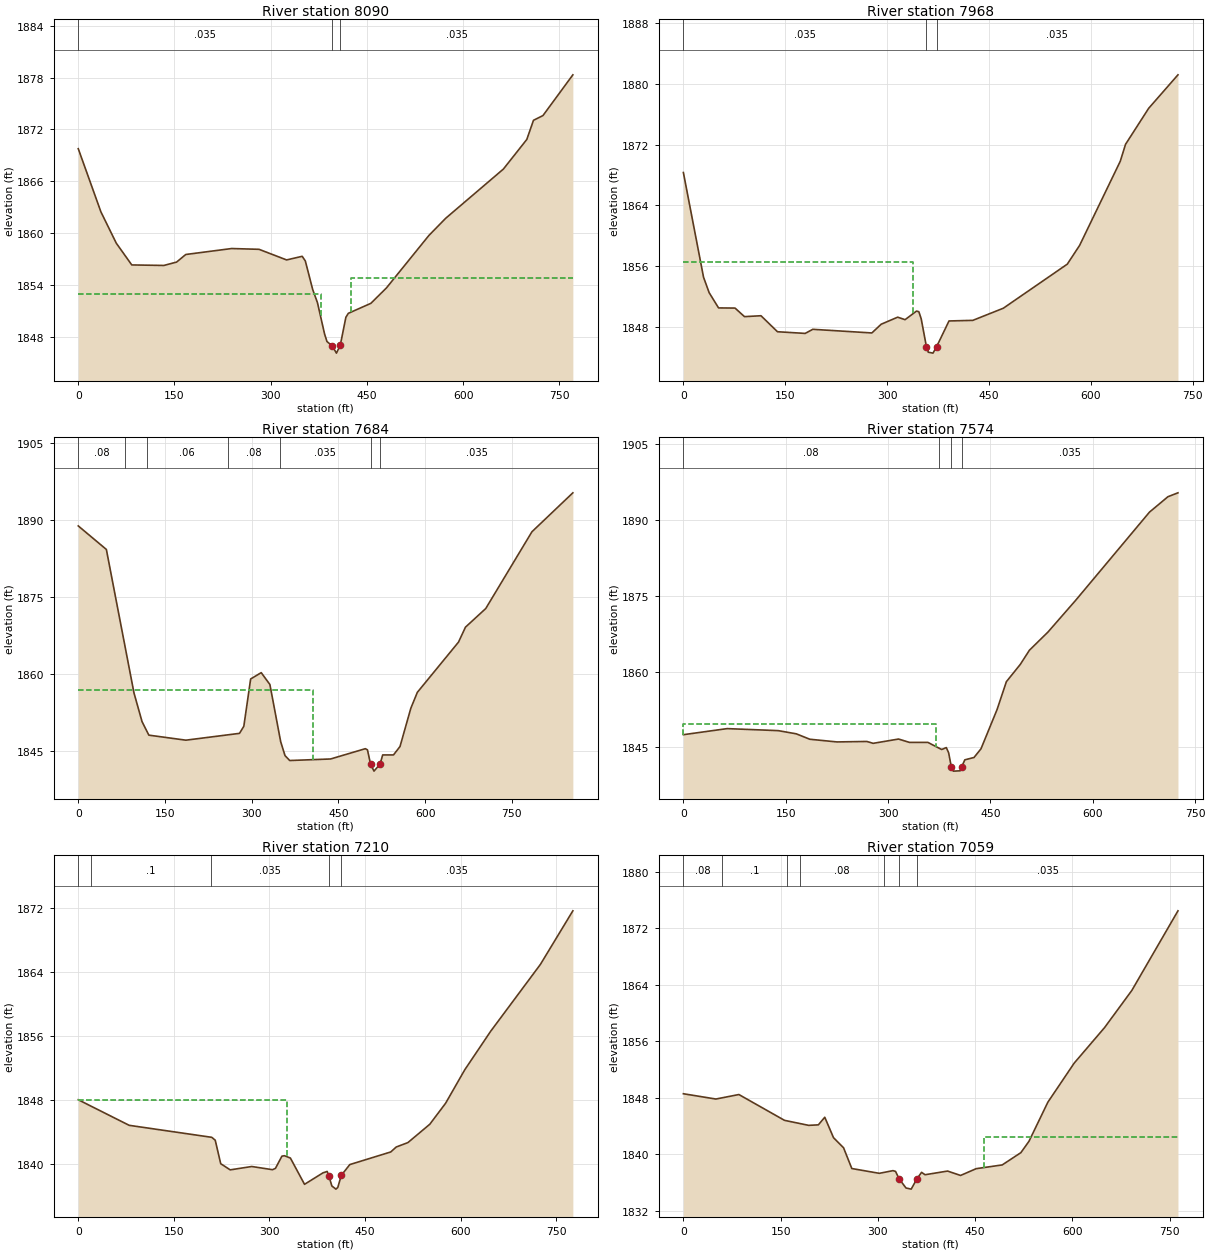
Type RM Length L Ch R = 1 ,8090    ,124.1,121.6,118.7
XS GIS Cut Line= 4
2043808.25026008151300.7277727392043949.03700808151417.719577416
2044212.76429659 151554.540501532044470.54284926151689.378513699
#Sta/Elev= 30
       0 1869.77    35.3 1862.45    59.2 1858.83    83.4  1856.3   133.4 1856.24
   153.3 1856.63   167.6 1857.51   239.1  1858.2   281.8 1858.11   324.8 1856.88
   349.1  1857.3     354 1856.76   365.5 1853.45   372.9 1851.93     384  1848.3
   387.7 1847.43   395.8 1846.92   402.5 1846.08  408.49 1846.99   417.2 1850.23
     421 1850.69   456.2 1851.85   480.5 1853.64   546.7 1859.72   572.9 1861.71
   662.8 1867.41   699.3 1870.84   709.7 1873.06   724.5 1873.61   771.1 1878.33
#Mann= 3 , 0 , 0
       0    .035       0   395.8    .045       0  408.49    .035       0
#XS Ineff= 2 , 0
          378.22 1852.96  425.21         1854.81
Permanent Ineff=
       F       F
Bank Sta=395.8,408.49
XS Rating Curve= 0 ,0
Exp/Cntr(USF)=0,0
Exp/Cntr=0.3,0.1

Type RM Length L Ch R = 1 ,7968    ,281.1,284.5,286.1
XS GIS Cut Line= 3
     2043750.347      151510.505     2044094.388      151629.142
     2044440.659      151742.801
#Sta/Elev= 30
       0 1868.33    29.7 1854.53    37.9  1852.5    51.8 1850.48    76.1 1850.46
      90 1849.33   114.3 1849.45   138.6 1847.34   179.4 1847.12   190.6 1847.66
   277.6 1847.18   291.3 1848.33   315.6 1849.26   326.5 1848.93   343.3 1850.06
   346.8 1849.98   350.3 1849.03  358.021845.335   360.7 1844.64   367.6 1844.52
  372.791845.338   391.2 1848.76   426.3 1848.84   471.2 1850.44   565.4 1856.25
   583.6 1858.73   643.4 1869.81   651.2 1872.05   685.3  1876.8   728.4 1881.21
#Mann= 3 ,-1 , 0
       0    .035       0  358.02    .045       0  372.79    .035       0
#XS Ineff= 2 , 0
          338.11  1856.5
Permanent Ineff=
       F       F
Bank Sta=358.02,372.79
XS Rating Curve= 0 ,0
Exp/Cntr=0.3,0.1

Type RM Length L Ch R = 1 ,7684    ,113.9,110.3,106.9
XS GIS Cut Line= 3
     2043602.805      151625.124     2043685.094      151710.067
     2044329.801      152067.832
#Sta/Elev= 30
       0 1888.86    48.6 1884.27    96.4 1856.26   110.3 1850.68   122.1 1848.03
   186.2 1847.05   278.9 1848.38   286.4 1849.76   298.2 1858.99   316.5 1860.23
   331.5 1857.91   350.2 1846.74   357.7 1844.03   365.8 1843.08   436.5 1843.38
   496.6 1845.39   500.3 1845.16  505.671842.357   511.6 1841.01  522.161842.391
   526.6 1844.17   545.3 1844.17   556.6 1845.82   575.3 1853.28   586.6 1856.39
   657.8 1866.19   669.8  1869.1   704.9 1872.74   784.8 1887.72   855.6 1895.32
#Mann= 7 ,-1 , 0
       0     .08       0      80     .04       0  118.27     .06       0
  258.27     .08       0  348.27    .035       0  505.67    .045       0
  522.16    .035       0
#XS Ineff= 2 , 0
          406.44 1856.93
Permanent Ineff=
       F       F
Bank Sta=505.67,522.16
XS Rating Curve= 0 ,0
Exp/Cntr=0.3,0.1

Type RM Length L Ch R = 1 ,7574    ,357.4,363.5,369.2
XS GIS Cut Line= 3
     2043615.826      151946.304     2043937.006      151991.877
     2044325.461      152089.533
#Sta/Elev= 30
       0 1847.53    64.2 1848.73     139 1848.33   165.5  1847.7   185.3 1846.63
   225.1  1846.1     269 1846.19   278.1 1845.82   315.4 1846.67   331.3 1846.01
   358.3 1846.01   378.6  1844.6   385.4 1844.98   388.8 1843.95  392.791841.108
   395.6 1840.33   405.7 1840.39  407.711841.104   412.5 1842.56     426 1843.03
   436.2 1844.74   459.8 1852.51   473.4    1858   493.7  1861.4   507.2 1864.22
   534.3  1867.8   574.9 1874.07   683.1  1891.5   710.2 1894.55   724.9 1895.32
#Mann= 4 ,-1 , 0
       0     .08       0   374.4    .035       0  392.79    .045       0
  407.71    .035       0
#XS Ineff= 2 , 0
           370.2 1849.65
Permanent Ineff=
       F       F
Bank Sta=392.79,407.71
XS Rating Curve= 0 ,0
Exp/Cntr=0.3,0.1

Type RM Length L Ch R = 1 ,7210    ,154.4,151.2,149.3
XS GIS Cut Line= 3
     2043619.526      152064.697     2043737.201      152136.256
     2044223.807      152549.311
#Sta/Elev= 30
       0 1848.04    79.9 1844.84   209.4 1843.34   214.9 1842.98   223.5 1840.04
   238.4 1839.27   272.2 1839.69   304.8 1839.29   309.4 1839.46   319.5 1840.98
   323.4 1841.04   332.8 1840.75     355 1837.46     384  1838.9   390.5 1839.07
     3931838.564   397.9 1837.25   404.3 1836.86   407.2 1837.07   412.71838.584
     426 1839.93   490.3 1841.51   498.9 1842.13   517.2 1842.68   551.6 1844.98
   576.4 1847.61   606.5  1851.8     647  1856.6   725.1 1864.97     776 1871.67
#Mann= 5 ,-1 , 0
       0     .08       0      20      .1       0  207.72    .035       0
     393    .045       0   412.7    .035       0
#XS Ineff= 2 , 0
          327.42 1848.05
Permanent Ineff=
       F       F
Bank Sta=393,412.7
XS Rating Curve= 0 ,0
Exp/Cntr=0.3,0.1

Type RM Length L Ch R = 1 ,7059    ,206.9,212.5,198.8
XS GIS Cut Line= 4
2043544.44705152152170.8127913712043742.32740636152323.028448941
2043947.23309924152467.0478787962044154.48057147152628.630653755
#Sta/Elev= 30
       0 1848.57    50.2 1847.82    85.6 1848.46     156  1844.8   193.3 1844.09
   208.2 1844.16   218.1 1845.24   231.6 1842.34   247.1 1840.91   259.8 1837.97
   302.2 1837.29   323.4 1837.67   327.3 1837.56  332.681836.525   343.4 1835.21
   351.4 1835.05  360.411836.526   367.4 1837.43   372.8 1837.09   407.5 1837.61
   427.6 1836.99   451.7 1837.95   491.8 1838.48   520.6 1840.22   533.1 1841.83
   562.2 1847.37   602.8 1852.91   649.7 1857.95   691.7 1863.21   762.9  1874.5
#Mann= 7 ,-1 , 0
       0     .08       0      60      .1       0     160     .06       0
     180     .08       0  309.65    .035       0  332.68    .045       0
  360.41    .035       0
#XS Ineff= 2 , 0
                          464.18         1842.45
Permanent Ineff=
       F       F
Bank Sta=332.68,360.41
XS Rating Curve= 0 ,0
Exp/Cntr(USF)=0,0
Exp/Cntr=0.5,0.3

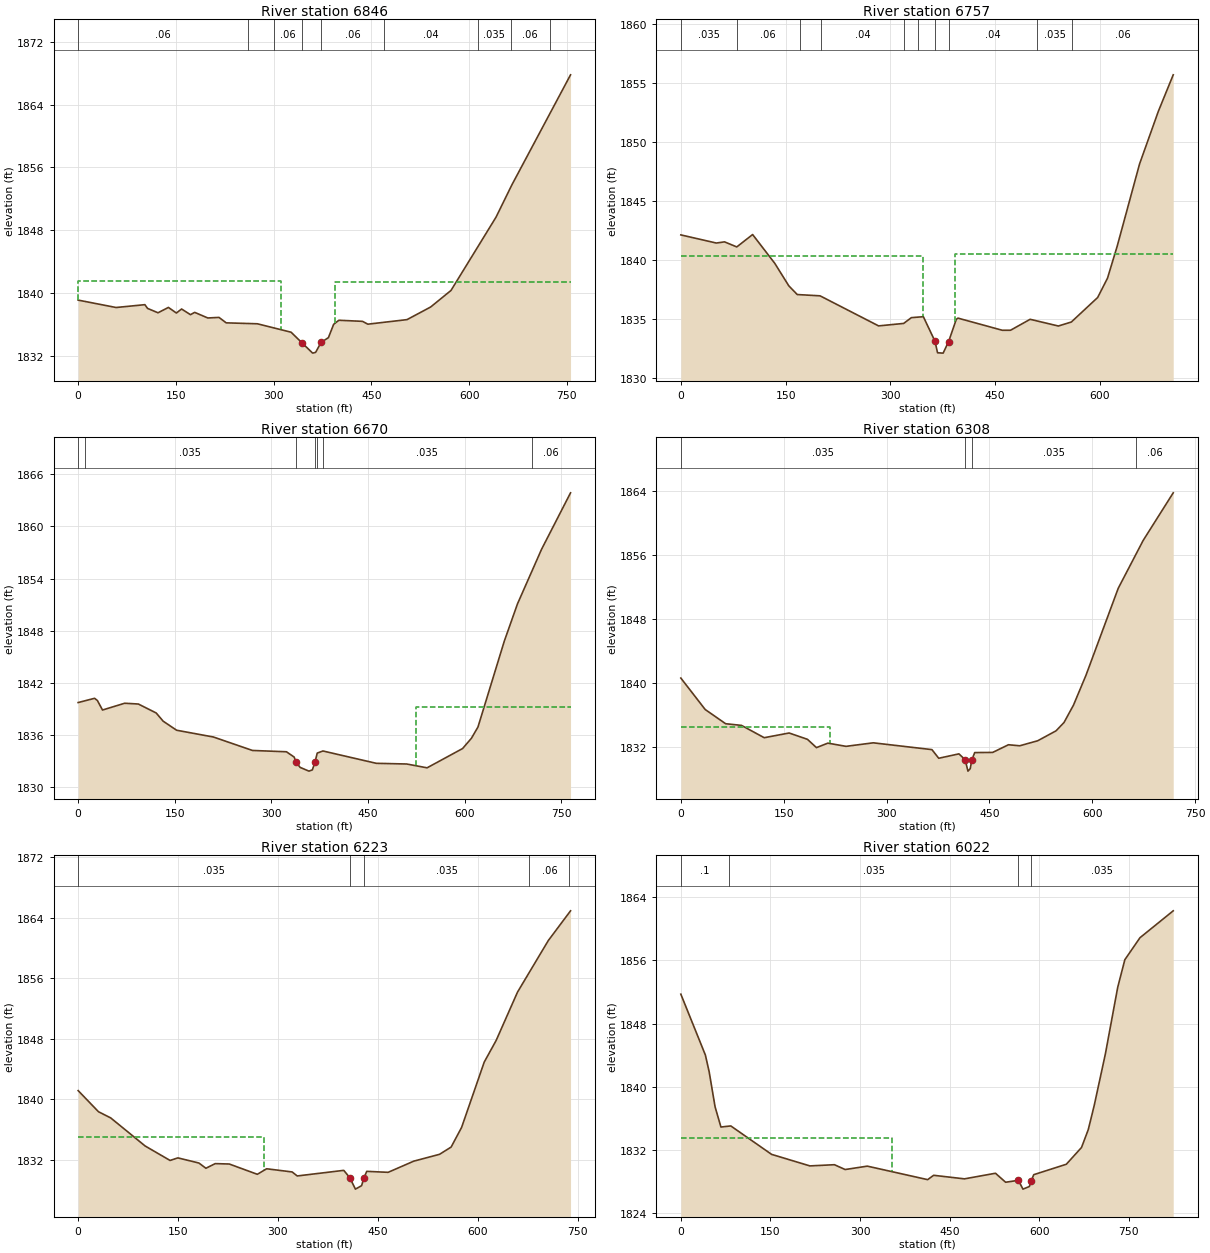
Type RM Length L Ch R = 1 ,6846    ,91.2,89.3,97.1
XS GIS Cut Line= 3
     2043479.588      152295.276     2043939.157      152621.267
     2044112.489      152703.958
#Sta/Elev= 30
       0 1839.14    58.2  1838.2   102.4 1838.56   106.4 1838.09   122.5 1837.53
   138.5 1838.21   150.7  1837.5   158.7 1838.01   172.3 1837.29   178.8 1837.58
   198.9 1836.87   216.1 1836.94   227.1 1836.25     275 1836.13   326.7 1835.06
  343.311833.718   359.8  1832.4   364.4  1832.5  372.611833.756     384 1834.37
     392 1836.06   400.1 1836.58   436.3 1836.44   444.5 1836.08   504.6 1836.66
   540.8 1838.26   572.1 1840.37   641.2 1849.69   665.3 1853.76   755.5 1867.78
#Mann= 9 ,-1 , 0
       0     .06       0     260    .035       0     300     .06       0
  343.31    .045       0  372.61     .06       0     470     .04       0
  613.45    .035       0  663.45     .06       0  723.45    .035       0
#XS Ineff= 2 , 0
          311.75 1841.53  394.27         1841.45
Permanent Ineff=
       F       F
Bank Sta=343.31,372.61
XS Rating Curve= 0 ,0
Exp/Cntr=0.5,0.3

Type RM Length L Ch R = 1 ,6757    ,89,87.4,86.6
XS GIS Cut Line= 2
     2043430.292      152368.425     2044005.945      152775.517
#Sta/Elev= 30
       0 1842.13    50.8 1841.44    62.5 1841.54    80.1 1841.11   102.8 1842.16
   134.5 1839.72   154.6 1837.81   166.7 1837.07   199.4 1836.96   283.2 1834.41
   319.1 1834.62   330.1 1835.11   347.3 1835.19  364.031833.094   367.6 1832.13
   375.6  1832.1  383.46 1833.08   394.4 1834.96   396.8 1835.07   460.3 1834.04
   472.1 1834.04   500.2 1834.97   540.6  1834.4   559.2 1834.74   596.9 1836.82
     611 1838.46   624.8 1841.16   656.9 1848.15   683.9 1852.63   705.1 1855.71
#Mann= 10 ,-1 , 0
       0    .035       0      80     .06       0     170    .035       0
     200     .04       0     320     .06       0     340     .04       0
  364.03    .045       0  383.46     .04       0     510    .035       0
     560     .06       0
#XS Ineff= 2 ,-1
       0  347.28 1840.35  393.12     705 1840.47
Permanent Ineff=
       F       F
Bank Sta=364.03,383.46
XS Rating Curve= 0 ,0
Exp/Cntr=0.5,0.3

Type RM Length L Ch R = 1 ,6670    ,349.6,361.3,287.8
XS GIS Cut Line= 3
     2043384.176      152449.525     2043875.549      152783.468
     2044039.339      152829.584
#Sta/Elev= 30
       0 1839.71    25.5  1840.2    29.9 1839.94    37.8 1838.85    72.2 1839.63
    93.4 1839.54   121.1 1838.51     132 1837.56   152.9 1836.52     210 1835.74
   270.6 1834.19   323.3 1834.04   335.3 1833.43  338.241832.834   344.6 1832.24
   358.2 1831.81   363.5 1831.95  367.531832.811   371.1 1833.89     380 1834.13
   462.7 1832.71     510 1832.63   541.6 1832.19   596.7 1834.41   610.4 1835.59
   620.6 1836.89   661.5 1846.79   681.9 1851.07   719.4 1857.38   764.3 1863.87
#Mann= 7 ,-1 , 0
       0     .08       0      10    .035       0  338.24    .045       0
  367.53    .035       0     370     .04       0     380    .035       0
  704.11     .06       0
#XS Ineff= 2 , 0
                          523.69         1839.17
Permanent Ineff=
       F       F
Bank Sta=338.24,367.53
XS Rating Curve= 0 ,0
Exp/Cntr=0.3,0.1

Type RM Length L Ch R = 1 ,6308    ,90.7,85.3,78
XS GIS Cut Line= 4
 2043327.8324619152846.4161330472043638.11822541152803.093215124
2043848.87836666152799.5805461032044038.56249379152840.561684679
#Sta/Elev= 30
       0 1840.61    35.5 1836.68    65.3  1834.9    88.5 1834.69   121.6 1833.15
   157.9 1833.74   184.6 1832.95   197.8 1831.91   214.4 1832.47   240.9 1832.07
   280.6 1832.51   366.2 1831.66   376.1 1830.58   405.6 1831.13  414.751830.383
   418.7 1828.97     422 1829.27  424.471830.382   428.6 1831.29   454.8 1831.31
   477.8 1832.27   494.2 1832.14   520.5 1832.77   547.2 1834.01   558.8 1835.05
   572.6 1837.22   590.9 1840.97   637.9 1851.84   674.3 1857.83   718.1 1863.78
#Mann= 4 ,-1 , 0
       0    .035       0  414.75    .045       0  424.47    .035       0
  664.09     .06       0
#XS Ineff= 2 , 0
          216.95 1834.54
Permanent Ineff=
       F       F
Bank Sta=414.75,424.47
XS Rating Curve= 0 ,0
Exp/Cntr(USF)=0,0
Exp/Cntr=0.3,0.1

Type RM Length L Ch R = 1 ,6223    ,203.2,201.4,193.9
XS GIS Cut Line= 3
     2043347.602      153029.949     2043869.188      152832.764
     2044048.881      152859.798
#Sta/Elev= 30
       0 1841.15    30.5 1838.36    48.9 1837.54   100.6 1833.83     138 1831.92
   149.7 1832.26   181.3 1831.58   191.8 1830.89   205.8  1831.5   226.9 1831.45
     269 1830.09     283 1830.82   321.3  1830.4   328.9 1829.87   398.8 1830.61
  407.811829.648   416.3 1828.13   425.6 1828.59  428.991829.586   433.3 1830.48
   465.4 1830.35     504 1831.83   542.6 1832.73     560 1833.69   575.7 1836.28
   609.7 1844.92   627.6 1847.78   659.7 1854.17   705.9 1860.98   739.3 1864.91
#Mann= 5 ,-1 , 0
       0    .035       0  407.81    .045       0  428.99    .035       0
  677.61     .06       0  737.61    .035       0
#XS Ineff= 2 , 0
          279.66 1835.04
Permanent Ineff=
       F       F
Bank Sta=407.81,428.99
XS Rating Curve= 0 ,0
Exp/Cntr=0.3,0.1

Type RM Length L Ch R = 1 ,6022    ,157.6,161.3,154.8
XS GIS Cut Line= 3
     2043318.978      153222.363     2043408.029      153228.724
     2044072.734      152915.455
#Sta/Elev= 30
       0 1851.73    41.1 1844.02    47.4 1841.91    57.3 1837.47    67.1 1834.91
    83.6 1835.05   151.9 1831.45     216 1829.99   257.1 1830.14     275 1829.53
   312.1 1829.96   413.1 1828.25   423.1  1828.8   474.7 1828.35   526.6 1829.06
   543.6 1827.92     5651828.166   572.6 1827.05   583.3 1827.38  586.051828.033
   590.7 1828.88   645.2  1830.2   670.6 1832.32   681.9 1834.58   691.8 1837.62
   710.5 1844.15   731.2  1852.6   743.1 1856.09   768.5 1858.88   824.1 1862.28
#Mann= 4 ,-1 , 0
       0      .1       0      80    .035       0     565    .045       0
  586.05    .035       0
#XS Ineff= 2 , 0
          353.87 1833.47
Permanent Ineff=
       F       F
Bank Sta=565,586.05
XS Rating Curve= 0 ,0
Exp/Cntr=0.3,0.1