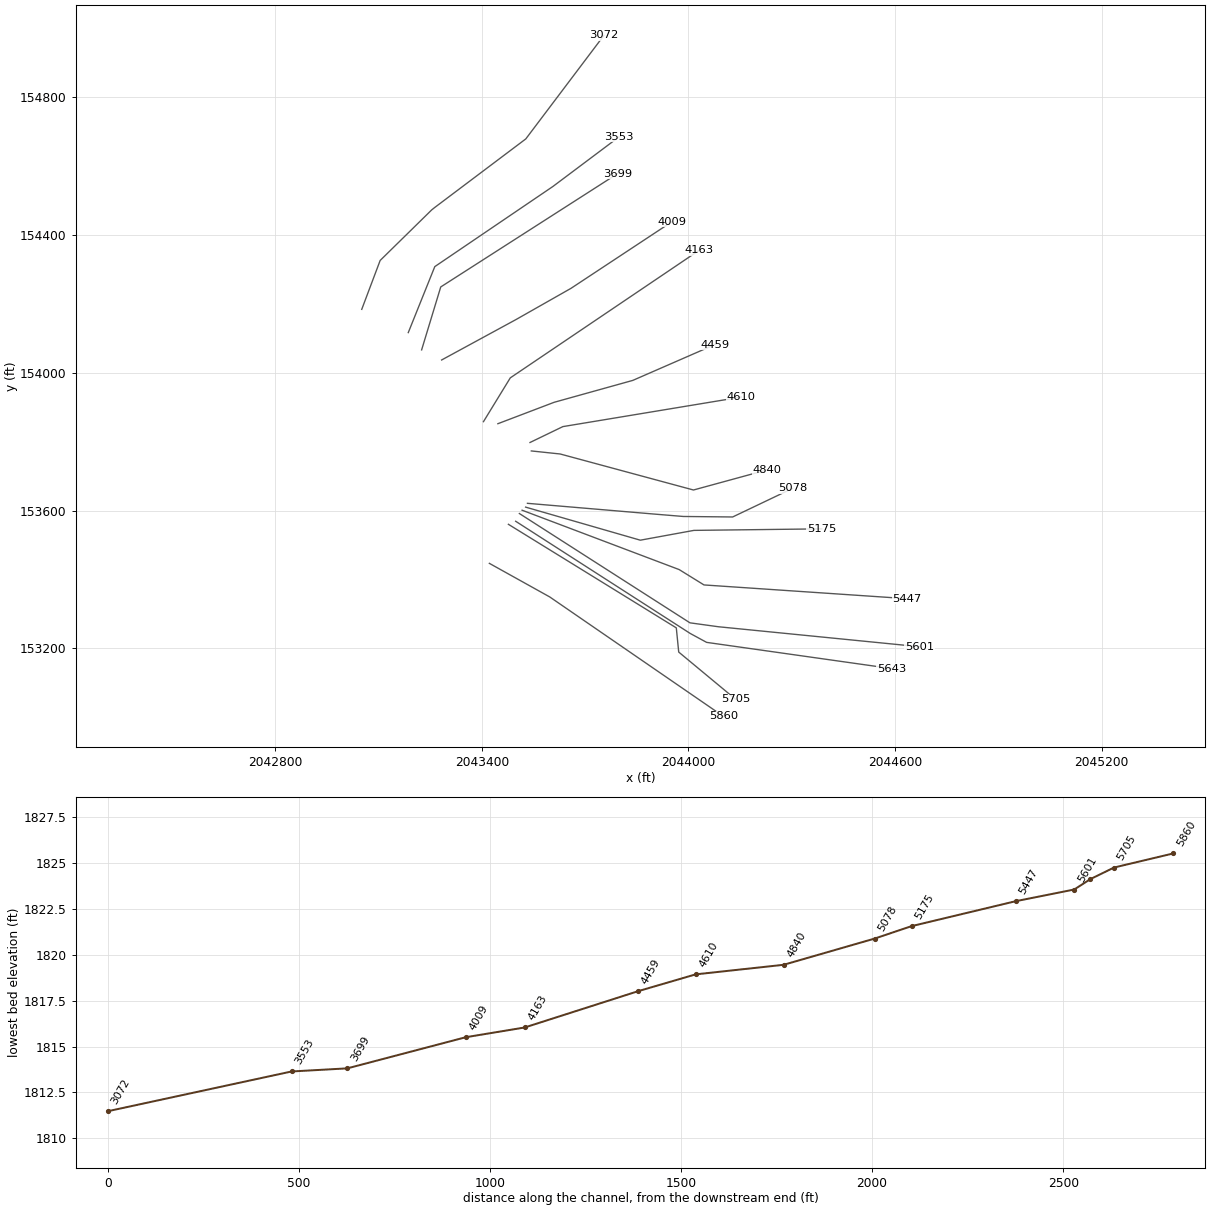
HEC-RAS study CRCKDCK.prj: CRCKDCK

--- CRCKDCK.g01 (geometry) --- (continued)

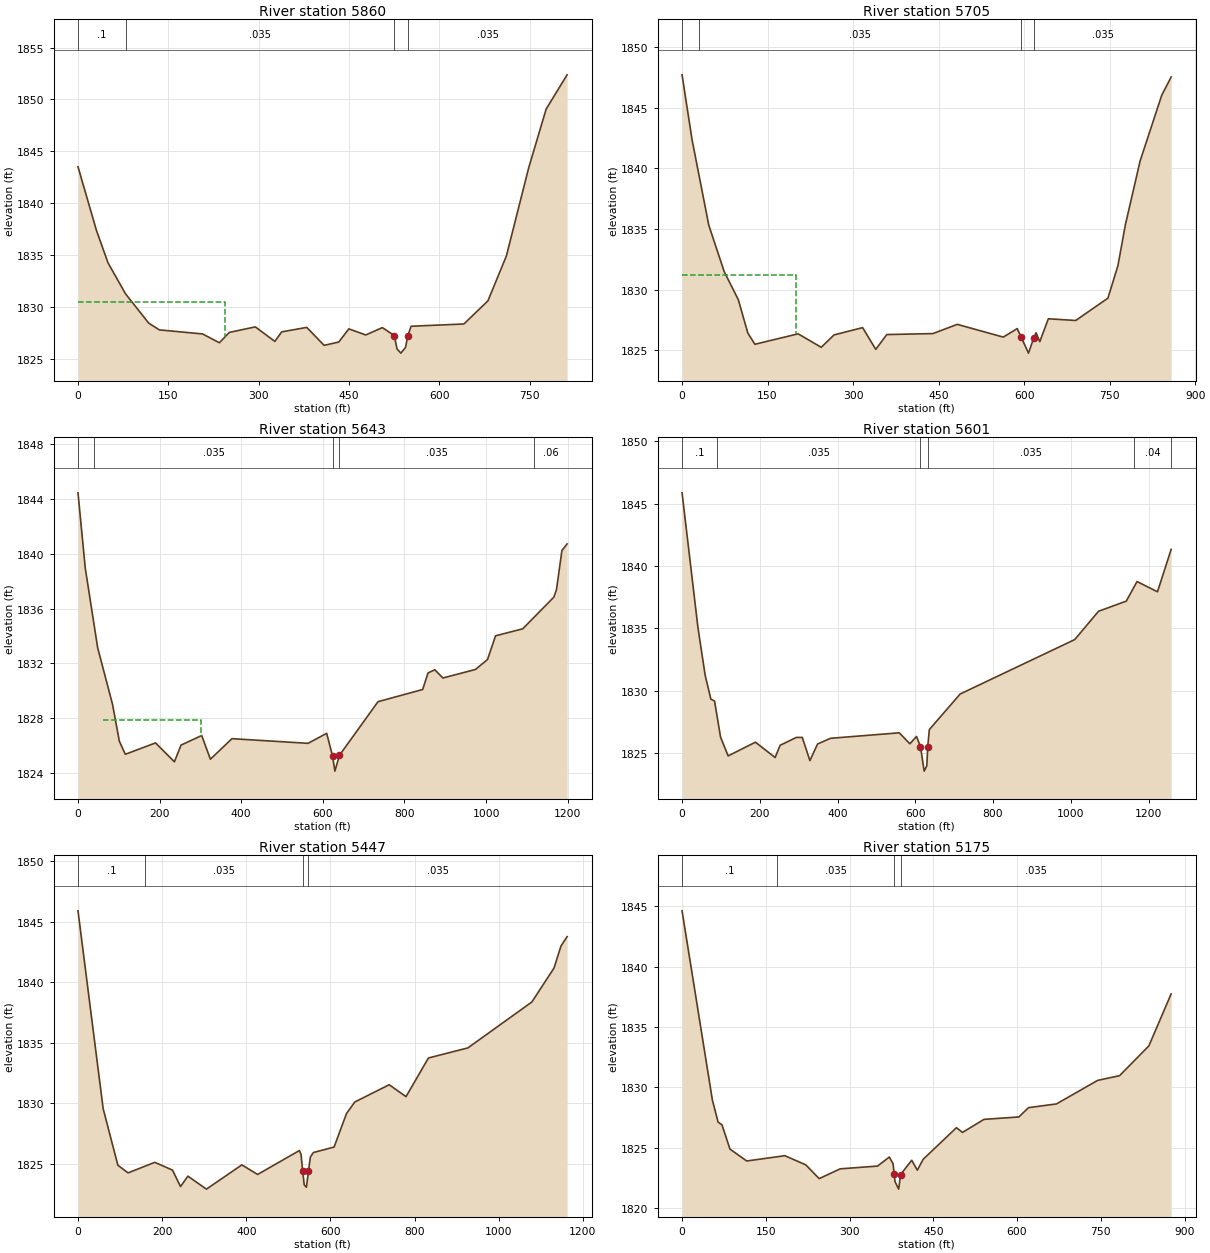
Type RM Length L Ch R = 1 ,5860    ,165.7,155.3,137.1
XS GIS Cut Line= 3
2043422.00566784153447.076918905     2043597.263       153349.58
     2044101.357      153002.916
#Sta/Elev= 30
       0 1843.51    30.6 1837.38    49.9 1834.24    78.9 1831.26   117.5 1828.43
   135.2 1827.78   206.9 1827.39   234.8 1826.54   251.4 1827.54   294.5 1828.07
   326.9 1826.67   338.3 1827.59   379.9 1828.02   408.8 1826.29   433.1 1826.61
   449.8 1827.88   477.9 1827.29   505.5    1828 525.4241827.233   529.8 1825.95
   536.2 1825.54     544 1826.09 547.7681827.237   553.3 1828.13   640.9 1828.35
   680.8 1830.58   711.5 1834.91   748.4 1843.38   777.5 1849.07   812.3 1852.37
#Mann= 4 ,-1 , 0
       0      .1       0      80    .035       0 525.424    .045       0
 547.768    .035       0
#XS Ineff= 2 , 0
          244.07 1830.43
Permanent Ineff=
       F       F
Bank Sta=525.424,547.768
XS Rating Curve= 0 ,0
Exp/Cntr=0.3,0.1

Type RM Length L Ch R = 1 ,5705    ,55.3,61.8,79
XS GIS Cut Line= 4
2043477.28873887153560.4323655792043964.79644435153259.740187833
2043971.82178239153189.4868074172044136.91722637153052.492715604
#Sta/Elev= 30
       0  1847.7    17.6 1842.34    46.9 1835.31    73.9 1831.49    98.7 1829.17
   115.4 1826.42   127.8  1825.5   203.6 1826.36   244.1 1825.25   266.6 1826.27
   316.7 1826.87   339.8 1825.08   359.1  1826.3     440 1826.38   482.7 1827.14
   563.4 1826.09   587.9 1826.79 594.8351826.083   607.7 1824.77 616.8161826.014
   620.9 1826.45   627.5 1825.72   642.5  1827.6   690.5 1827.46     747  1829.3
   764.6 1831.99   777.6 1835.35   803.5 1840.61   841.3 1846.01   857.9 1847.52
#Mann= 4 ,-1 , 0
       0      .1       0      30    .035       0 594.835    .045       0
 616.816    .035       0
#XS Ineff= 2 , 0
          199.14 1831.18
Permanent Ineff=
       F       F
Bank Sta=594.835,616.816
XS Rating Curve= 0 ,0
Exp/Cntr(USF)=0,0
Exp/Cntr=0.5,0.3

Type RM Length L Ch R = 1 ,5643    ,39.7,42.5,47.9
XS GIS Cut Line= 4
 2043498.3709117153569.2894903652044005.47645328153243.366529383
2044052.89521145153217.614608672 2044589.4660396153141.653509253
#Sta/Elev= 30
       0 1844.46    17.8 1838.97    48.2 1833.15    84.7 1829.01   101.3 1826.33
     116 1825.37   190.1  1826.2   236.3 1824.82   252.5 1826.04   303.2 1826.74
   324.5 1825.01   377.3 1826.51   563.9 1826.17   609.5  1826.9 624.0091825.218
   629.6 1824.14 640.7671825.296   735.3 1829.21   844.7  1830.1   857.9 1831.31
   874.5 1831.54   894.4 1830.94   973.9 1831.56  1003.7 1832.29  1023.3 1834.02
  1089.9 1834.53  1166.1 1836.84  1172.7 1837.39    1186 1840.25  1198.7 1840.73
#Mann= 5 ,-1 , 0
       0      .1       0      40    .035       0 624.009    .045       0
 640.767    .035       0 1116.77     .06       0
#XS Ineff= 3 ,-1
   62.22  301.631827.845  581.68  611.24 1825.31  649.66  676.26 1825.33
Permanent Ineff=
       F       F       F
Bank Sta=624.009,640.767
XS Rating Curve= 0 ,0
Exp/Cntr(USF)=0,0
Exp/Cntr=0.5,0.3

Type RM Length L Ch R = 1 ,5601    ,151.8,153.6,143.6
XS GIS Cut Line= 4
2043509.16812454 153591.734962772044004.44000234153274.387208778
2044086.95259764153263.0061611512044670.84776438153205.061320749
#Sta/Elev= 30
       0 1845.87    40.9 1835.07    59.5 1831.24    74.1 1829.34    83.6 1829.19
    99.1 1826.29   118.6 1824.79   188.8 1825.89   239.4 1824.66   252.3 1825.64
     294 1826.27   309.3 1826.27     329 1824.41   348.5 1825.74   381.8  1826.2
   558.9 1826.64   586.2 1825.76   603.1 1826.35   613.4 1825.54   622.9 1823.57
   629.6 1823.99   632.1 1825.54   636.2  1826.9   715.5 1829.75  1010.2 1834.11
  1071.5 1836.38  1142.8 1837.19  1170.5 1838.76  1223.1 1837.94  1258.3 1841.34
#Mann= 6 ,-1 , 0
       0      .1       0      90    .035       0   613.4    .045       0
   632.1    .035       0 1161.51     .04       0 1258.28     .06       0
#XS Ineff= 2 ,-1
  578.79  589.16 1825.63  646.78  662.91 1825.65
Permanent Ineff=
       F       F
Bank Sta=613.4,632.1
XS Rating Curve= 0 ,0
Exp/Cntr(USF)=0,0
Exp/Cntr=0.5,0.3

Type RM Length L Ch R = 1 ,5447    ,256.9,272.2,267.8
XS GIS Cut Line= 4
2043517.05368256153601.3653672192043973.14212137153428.979772386
2044045.22208967153384.4040025112044634.12042462153344.570335815
#Sta/Elev= 30
       0 1845.89    59.8 1829.57    94.8  1824.9     119 1824.27   182.5 1825.14
   224.6  1824.5   243.7 1823.14   261.2    1824   305.3 1822.93   389.5 1824.93
     427 1824.14   526.1 1826.11   530.1 1825.81     534 1824.44   537.8 1823.27
   542.9 1823.09  547.83 1824.41   552.4 1825.58   559.5 1825.95   608.7  1826.4
   638.3 1829.17     658 1830.12   739.7 1831.54   779.7 1830.56     833 1833.75
   926.7 1834.58  1078.9 1838.37  1131.5 1841.17    1148 1842.98  1162.6 1843.76
#Mann= 4 ,-1 , 0
       0      .1       0     160    .035       0     534    .045       0
  547.83    .035       0
Bank Sta=534,547.83
XS Rating Curve= 0 ,0
Exp/Cntr(USF)=0,0
Exp/Cntr=0.3,0.1

Type RM Length L Ch R = 1 ,5175    ,99.8,96.8,91.4
XS GIS Cut Line= 4
2043527.25355195153610.3455439642043860.28006573153514.337629592
2044015.82104997153542.7902486612044387.12423542153547.256478026
#Sta/Elev= 30
       0 1844.63    54.4 1828.93    64.6 1827.12    71.5  1826.9    85.8 1824.89
   115.8  1823.9   184.1 1824.34   221.7 1823.58   245.6 1822.44   283.2 1823.25
   350.1 1823.48   371.3 1824.23     378 1823.66  379.98  1822.8   381.4 1822.19
     388 1821.57   391.4 1822.78   411.4 1823.96   421.4 1823.14   431.8 1824.04
   491.4 1826.66   502.3 1826.27   540.8 1827.35   603.2 1827.55   620.5 1828.32
   670.6 1828.63   744.3 1830.58   783.6 1830.97   836.1 1833.44     876 1837.75
#Mann= 4 ,-1 , 0
       0      .1       0     170    .035       0  379.98    .045       0
   391.4    .035       0
Bank Sta=379.98,391.4
XS Rating Curve= 0 ,0
Exp/Cntr(USF)=0,0
Exp/Cntr=0.3,0.1

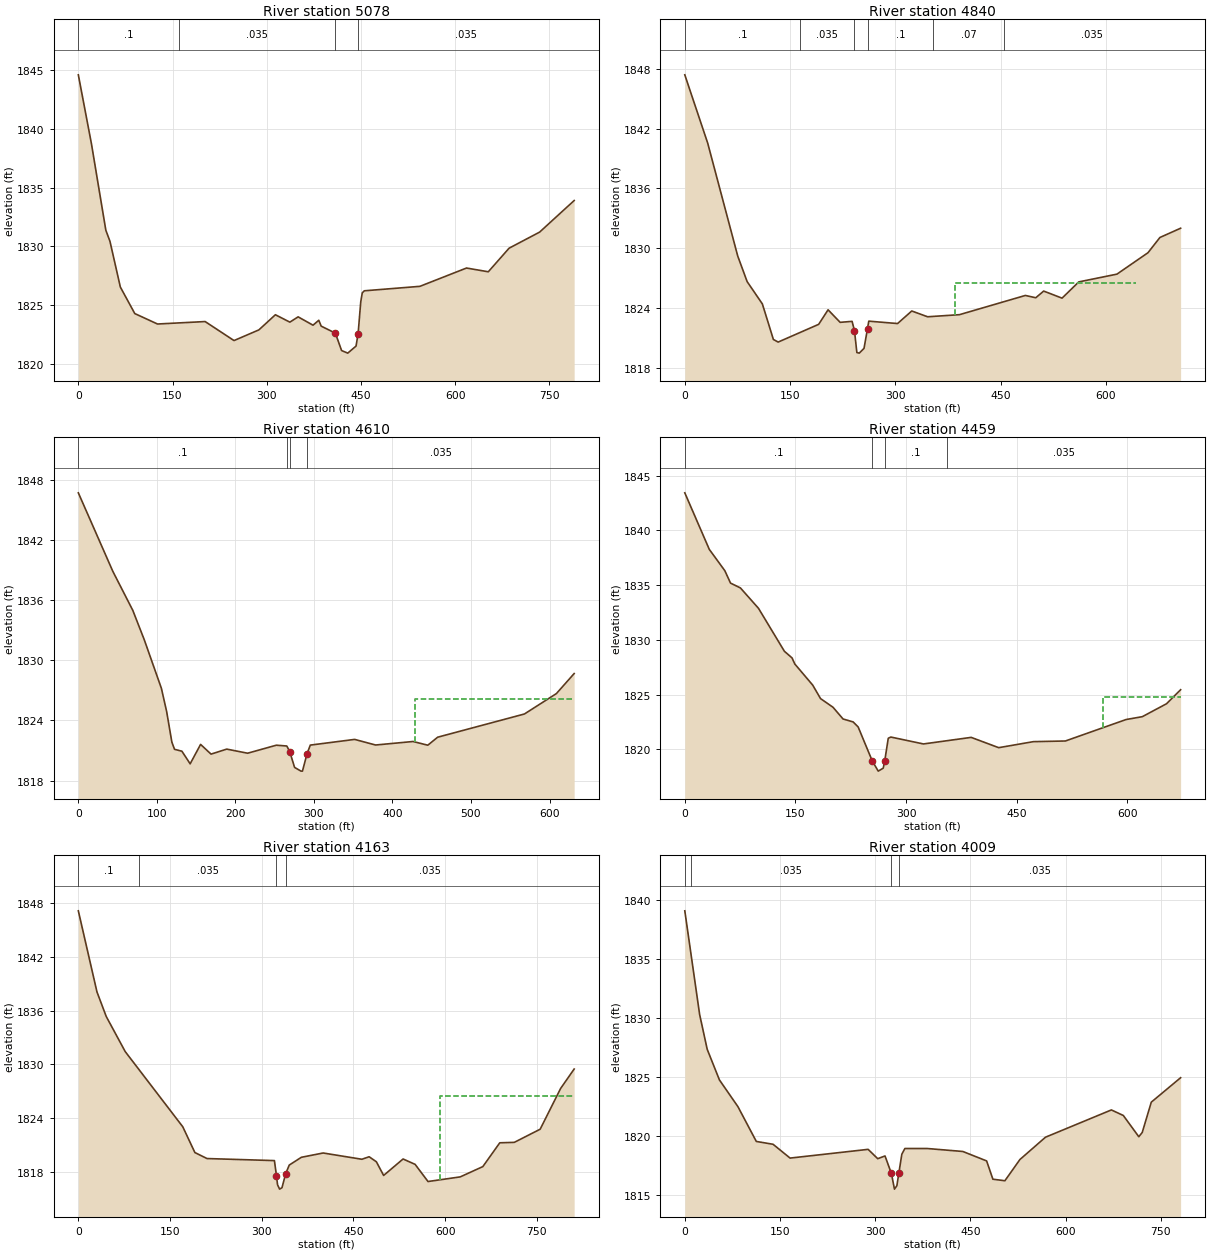
Type RM Length L Ch R = 1 ,5078    ,223.6,238,243.8
XS GIS Cut Line= 5
2043532.58360151153621.3827402752043904.55853194153589.846997143
2043985.17428597153583.208052693     2044128.391      153581.749
     2044301.723       153664.44
#Sta/Elev= 30
       0  1844.6    20.8 1838.75    43.8 1831.36    50.4 1830.41    66.9 1826.52
    89.9 1824.26   126.1 1823.37   201.9 1823.58   247.9 1821.96   287.5 1822.87
   313.8 1824.16   336.8 1823.53     350 1823.98   373.7 1823.27   382.9 1823.69
   386.7 1823.19 409.2781822.592   419.2 1821.11     429 1820.89   442.2 1821.49
  445.491822.547   449.7 1825.26   452.1 1826.02   455.4  1826.2   543.9 1826.58
   618.1 1828.14   652.8 1827.82   685.9 1829.83   734.5  1831.2   789.5 1833.89
#Mann= 4 ,-1 , 0
       0      .1       0     160    .035       0 409.278    .045       0
  445.49    .035       0
Bank Sta=409.278,445.49
XS Rating Curve= 0 ,0
Exp/Cntr=0.3,0.1

Type RM Length L Ch R = 1 ,4840    ,216,229.8,229
XS GIS Cut Line= 4
2043543.85905163 153773.471047142043627.60788575153764.634817905
2044014.66173949153660.0679348732044227.99595156153718.309356876
#Sta/Elev= 30
       0  1847.4    32.6 1840.55    75.4 1829.21    88.8 1826.64   110.5  1824.4
   126.2 1820.83     133 1820.57   190.7 1822.35   204.1 1823.81   221.3 1822.55
   238.3 1822.65   241.7 1821.72   245.1 1819.52   248.5 1819.46   255.3 1819.94
   260.3 1821.92   262.1 1822.67   303.1 1822.43   323.3 1823.69   345.9 1823.11
   391.2 1823.32   485.1 1825.25     500 1825.02   511.2 1825.69   537.4 1824.98
   561.2 1826.61   615.6 1827.39   659.8 1829.54   676.8 1831.07   706.3    1832
#Mann= 6 ,-1 , 0
       0      .1       0  164.21    .035       0   241.7    .045       0
   260.3      .1       0  354.21     .07       0  454.21    .035       0
#XS Ineff= 1 ,-1
  385.01   642.61826.458
Permanent Ineff=
       F
Bank Sta=241.7,260.3
XS Rating Curve= 0 ,0
Exp/Cntr(USF)=0,0
Exp/Cntr=0.3,0.1

Type RM Length L Ch R = 1 ,4610    ,144.5,151,153.3
XS GIS Cut Line= 3
     2043540.016      153798.016     2043635.428      153844.132
     2044153.834      153930.003
#Sta/Elev= 30
       0 1846.75    43.9 1838.91    69.4    1835      84 1832.06   105.8 1827.21
   112.5 1824.88   119.1 1821.84   122.5 1821.12   131.9 1820.93   142.4 1819.67
   155.7 1821.61     169 1820.64     189 1821.14   215.6 1820.73   252.1 1821.53
   265.5 1821.45   269.21820.889   275.4 1819.31   283.6 1818.94   285.4 1818.94
  291.171820.653   295.4 1821.54   351.9 1822.11   378.5 1821.55   426.2  1821.9
     445 1821.53   457.6 1822.33   568.1 1824.65   608.8 1826.69   631.4 1828.69
#Mann= 4 ,-1 , 0
       0      .1       0  265.97    .035       0   269.2    .045       0
  291.17    .035       0
#XS Ineff= 2 , 0
                          428.22         1826.19
Permanent Ineff=
       F       F
Bank Sta=269.2,291.17
XS Rating Curve= 0 ,0
Exp/Cntr=0.3,0.1

Type RM Length L Ch R = 1 ,4459    ,282.9,296.6,295.9
XS GIS Cut Line= 4
2043446.75094624153852.5573080442043610.09728342153914.715648742
2043838.49304692153978.3195322472044077.00761006154082.398614346
#Sta/Elev= 30
       0 1843.42    33.2 1838.26    54.3 1836.31      62 1835.18    75.4 1834.74
    99.9 1832.88     135 1828.96   145.4 1828.35   149.1  1827.8   173.4 1825.87
     184 1824.64   200.9 1823.85   214.5 1822.78   228.2 1822.51     235 1822.05
  254.031818.964   262.2 1818.02     269 1818.29  271.031818.963   275.8 1821.02
   279.3 1821.13   323.5  1820.5   388.2  1821.1   425.5 1820.16   472.5 1820.71
   515.9 1820.77   598.2 1822.73   620.2 1822.99     653 1824.17   672.1 1825.45
#Mann= 4 ,-1 , 0
       0      .1       0  254.03    .045       0  271.03      .1       0
  354.77    .035       0
#XS Ineff= 2 , 0
                          567.49          1824.8
Permanent Ineff=
       F       F
Bank Sta=254.03,271.03
XS Rating Curve= 0 ,0
Exp/Cntr(USF)=0,0
Exp/Cntr=0.3,0.1

Type RM Length L Ch R = 1 ,4163    ,152.1,153.9,151.3
XS GIS Cut Line= 3
     2043404.849      153858.444     2043482.769       153985.66
     2044031.388      154356.177
#Sta/Elev= 30
       0 1847.16    30.5 1838.09    45.7 1835.34    76.7 1831.42   170.9 1823.01
   190.7 1820.13   210.5 1819.46   320.8 1819.23  324.181817.549   325.9 1816.53
   329.3 1816.04   333.2  1816.2   339.31817.779   345.1 1818.73   364.9  1819.6
   400.5 1820.08   463.9 1819.38   475.8 1819.66   487.6  1819.1   499.5 1817.57
   531.3 1819.41     551 1818.81   572.1 1816.89   624.9 1817.41   661.8 1818.56
   689.5 1821.22   713.3 1821.27   755.6 1822.74     789 1827.29   811.2 1829.47
#Mann= 4 ,-1 , 0
       0      .1       0     100    .035       0  324.18    .045       0
   339.3    .035       0
#XS Ineff= 2 , 0
                          592.11         1826.43
Permanent Ineff=
       F       F
Bank Sta=324.18,339.3
XS Rating Curve= 0 ,0
Exp/Cntr=0.3,0.1

Type RM Length L Ch R = 1 ,4009    ,291.5,310.1,307.2
XS GIS Cut Line= 4
2043283.40460905154037.5867873322043498.79048729154154.675754693
2043659.24573886 154245.744951532043952.69092866154439.447687659
#Sta/Elev= 30
       0 1839.09    23.4  1830.3    35.3 1827.36    54.6 1824.76    83.7  1822.5
   112.7 1819.55   139.1 1819.31   165.9 1818.14   288.9 1818.88     304 1818.09
   315.5 1818.32  325.481816.849   330.4 1815.51   334.2  1815.8   337.2 1816.84
     342 1818.47   346.8 1818.95   382.3 1818.95   438.1  1818.7   475.6  1817.9
   485.5 1816.35   504.4 1816.22   528.1 1818.02   568.4 1819.91   672.2 1822.22
     691 1821.75   715.4 1819.95   720.8 1820.31   735.1 1822.88   781.3 1824.95
#Mann= 4 ,-1 , 0
       0     .12       0      10    .035       0  325.48    .045       0
   337.2    .035       0
Bank Sta=325.48,337.2
XS Rating Curve= 0 ,0
Exp/Cntr(USF)=0,0
Exp/Cntr=0.3,0.1

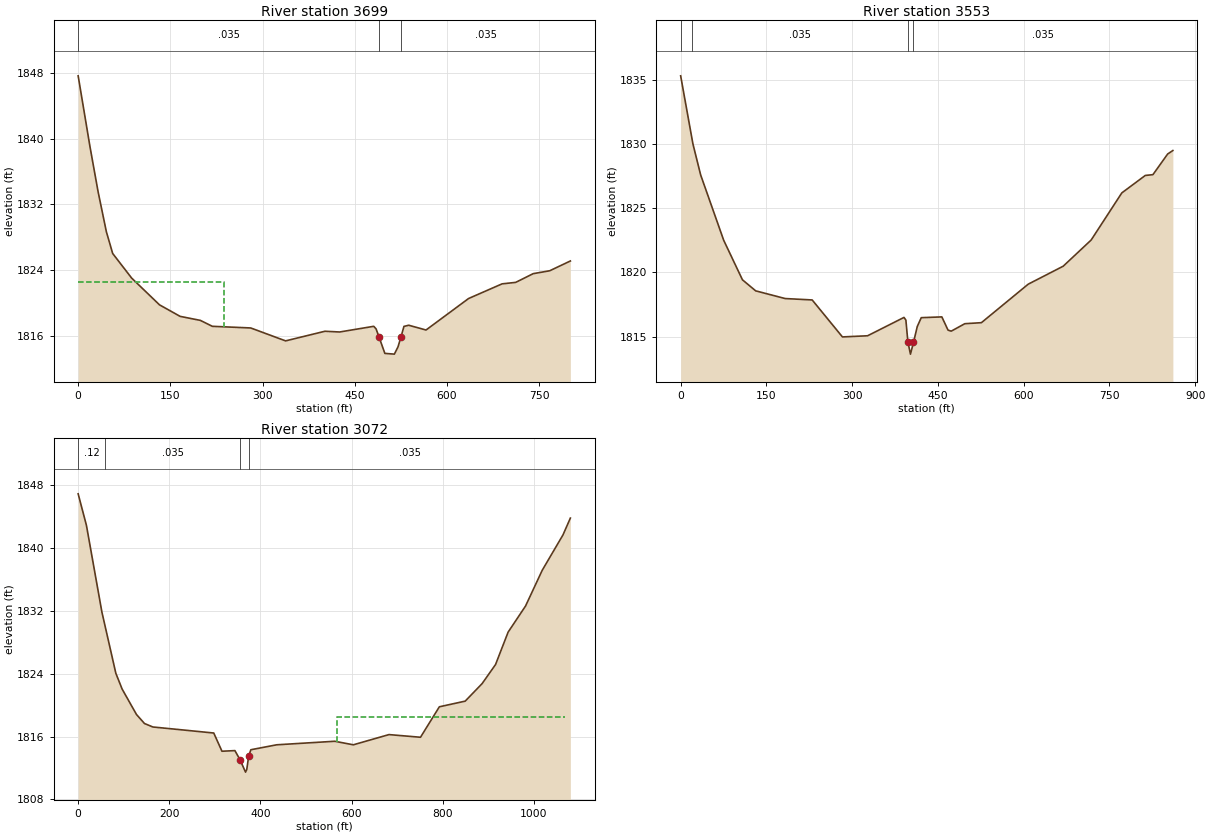
Type RM Length L Ch R = 1 ,3699    ,117.7,145.8,149.7
XS GIS Cut Line= 3
     2043225.318      154066.901     2043280.813      154249.634
     2043794.448      154578.805
#Sta/Elev= 30
       0 1847.63    19.3    1839    32.5 1833.53    45.9 1828.69    56.2 1826.04
    87.1 1823.05   132.4  1819.8   165.9  1818.4   198.9 1817.91   218.4 1817.19
   280.8 1816.99   337.6 1815.42   401.6 1816.59   425.5  1816.5     481 1817.19
   484.8 1816.88   489.41815.942   499.1  1813.9   514.6 1813.81   520.5 1814.69
   525.51815.945   530.2 1817.18     538 1817.32   566.1 1816.74   635.4 1820.57
   689.9 1822.35     712 1822.53   740.6 1823.59   767.4 1823.94     801 1825.13
#Mann= 3 ,-1 , 0
       0    .035       0   489.4    .045       0   525.5    .035       0
#XS Ineff= 2 , 0
          237.42 1822.57
Permanent Ineff=
       F       F
Bank Sta=489.4,525.5
XS Rating Curve= 0 ,0
Exp/Cntr=0.3,0.1

Type RM Length L Ch R = 1 ,3553    ,466.7,481.1,473
XS GIS Cut Line= 4
2043186.55324099154117.0916417132043263.54828479154308.683021366
2043606.50919502154541.3902284672043798.52470817154685.408046871
#Sta/Elev= 30
       0 1835.32    21.5 1830.01      35  1827.6    75.3 1822.51   108.1 1819.43
   131.2 1818.57   182.8 1817.97   230.1 1817.86     283 1814.98     327 1815.07
   390.7  1816.5     394 1816.29   397.5 1814.59     402 1813.64   407.3 1814.55
   413.9 1815.79   420.9 1816.48   456.9 1816.54   467.7 1815.51   473.3 1815.43
   497.1 1816.01   526.1 1816.09     608 1819.09   669.2 1820.49   718.1 1822.53
   771.7  1826.2   812.8 1827.56   826.1 1827.62   851.9 1829.23     861  1829.5
#Mann= 4 ,-1 , 0
       0     .12       0      20    .035       0   397.5    .045       0
   407.3    .035       0
Bank Sta=397.5,407.3
XS Rating Curve= 0 ,0
Exp/Cntr(USF)=0,0
Exp/Cntr=0.3,0.1

Type RM Length L Ch R = 1 ,3072    ,170.4,170.3,170.7
XS GIS Cut Line= 6
2043051.44242914154184.5932444262043104.91690862 154326.57713792
2043254.41128927154473.2348362752043262.18189673154479.502470163
2043527.82211666154679.5057453772043754.65156411154980.080697452
#Sta/Elev= 30
       0 1846.91    18.2 1842.89    52.1 1831.86    82.7 1824.06    96.5 1822.05
     128 1818.81   145.6 1817.66   163.9 1817.22   297.6 1816.45   315.6 1814.13
     344 1814.21   355.6 1813.01   367.3 1811.47     370  1811.8   374.3 1813.53
     379 1814.32   435.7 1814.95     563  1815.4   603.9 1814.95   682.1 1816.25
   751.3 1815.91   792.7 1819.79   849.4 1820.51   886.5 1822.74     916 1825.17
   943.6  1829.3   981.8 1832.62  1018.5 1837.18    1064 1841.68  1080.2 1843.82
#Mann= 4 ,-1 , 0
       0     .12       0      60    .035       0   355.6    .045       0
   374.3    .035       0
#XS Ineff= 1 ,-1
  569.05  1067.4 1818.55
Permanent Ineff=
       F
Bank Sta=355.6,374.3
XS Rating Curve= 0 ,0
Exp/Cntr(USF)=0,0
Exp/Cntr=0.3,0.1