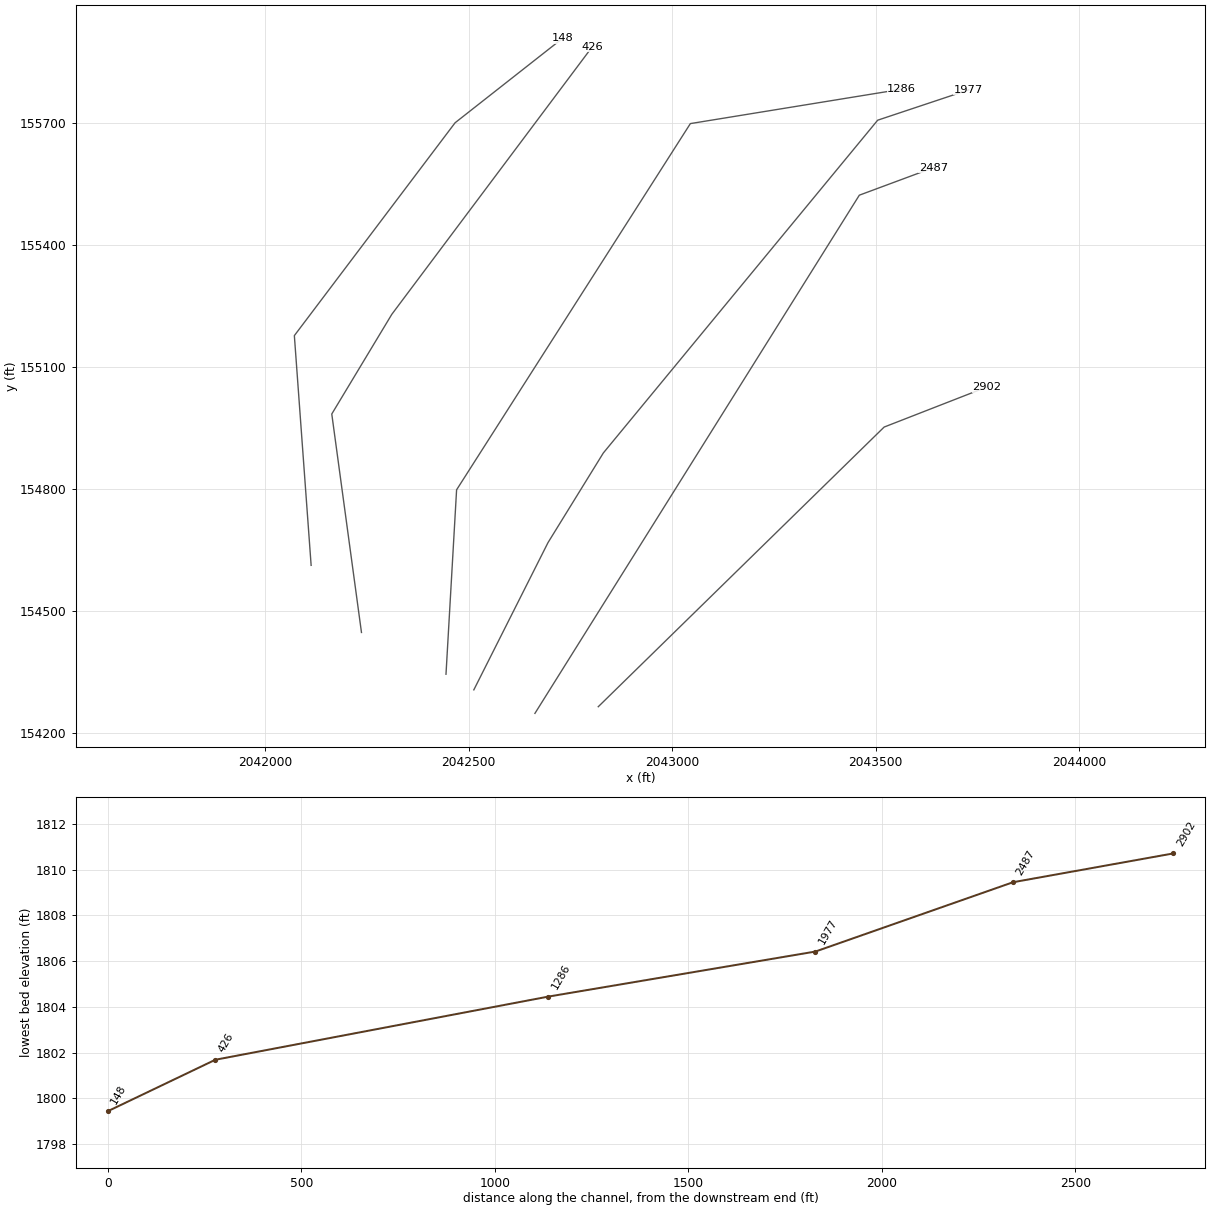
HEC-RAS study CRCKDCK.prj: CRCKDCK

--- CRCKDCK.g01 (geometry) --- (continued)

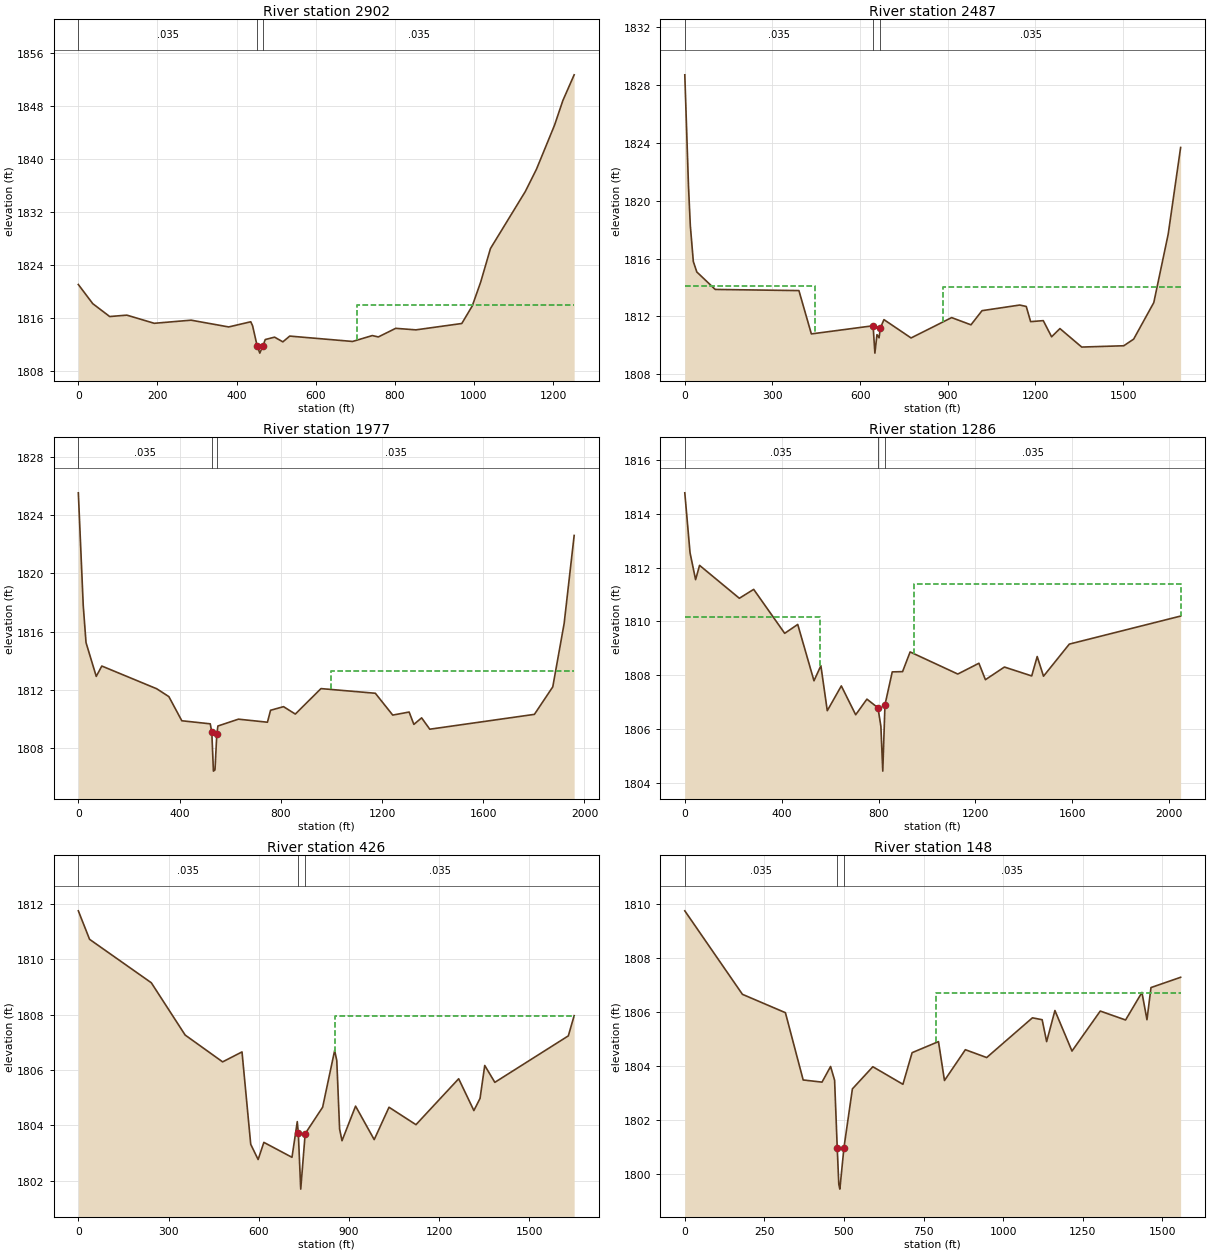
Type RM Length L Ch R = 1 ,2902    ,404.4,414.5,404.6
XS GIS Cut Line= 3
     2042818.487      154265.331     2043520.934      154952.503
     2043773.348      155050.922
#Sta/Elev= 30
       0 1821.06    36.5 1818.17    79.3 1816.23   122.7 1816.44   191.9 1815.21
   285.1 1815.68   380.2 1814.66   435.9 1815.44   440.6 1814.84  452.011811.826
   458.8 1810.71  466.921811.817   472.6 1812.76   496.2 1813.12   517.1 1812.41
   534.4 1813.28   693.4 1812.47   743.3 1813.36   758.4 1813.15   802.4 1814.45
   853.5 1814.22   969.5 1815.18   995.9 1817.82  1017.4 1821.45    1042 1826.49
  1130.1 1835.09  1158.3 1838.45  1203.9 1845.08  1225.1 1848.82  1253.6 1852.69
#Mann= 3 ,-1 , 0
       0    .035       0  452.01    .045       0  466.92    .035       0
#XS Ineff= 2 , 0
                          704.01         1817.94
Permanent Ineff=
       F       F
Bank Sta=452.01,466.92
XS Rating Curve= 0 ,0
Exp/Cntr=0.3,0.1

Type RM Length L Ch R = 1 ,2487    ,468.2,510.5,419.4
XS GIS Cut Line= 3
     2042662.888      154248.983      2043459.98      155522.276
     2043642.272      155589.984
#Sta/Elev= 30
       0 1828.72    12.6 1821.03    18.9 1818.28    29.2 1815.79    41.1 1815.07
   104.1 1813.86   390.5 1813.78   433.1 1810.78   644.41811.345   650.5 1809.45
   657.6 1810.73   664.8 1810.51   669.11811.187   681.5 1811.77   774.3  1810.5
   913.1 1811.91   979.3 1811.41  1017.1 1812.39  1146.3 1812.78  1168.5 1812.68
  1183.4 1811.63  1226.7  1811.7  1255.2 1810.58  1283.7 1811.15  1358.2 1809.87
  1502.2 1809.96    1536 1810.42  1604.9 1812.95  1654.2 1817.69  1696.7 1823.69
#Mann= 3 ,-1 , 0
       0    .035       0   644.4    .045       0   669.1    .035       0
#XS Ineff= 2 , 0
          446.69 1814.08  884.28         1814.05
Permanent Ineff=
       F       F
Bank Sta=644.4,669.1
XS Rating Curve= 0 ,0
Exp/Cntr=0.3,0.1

Type RM Length L Ch R = 1 ,1977    ,608,690.3,585.8
XS GIS Cut Line= 5
2042512.73895692154306.7891241992042694.98189275154668.554952056
2042830.98408368154888.8785013532043505.10265911155706.558850059
2043728.59854377155781.052873812
#Sta/Elev= 30
       0 1825.54    19.4  1817.8    30.4 1815.25    70.8 1812.93    92.8 1813.64
   309.6 1812.08   357.7 1811.54   408.9 1809.88   521.3 1809.67   527.5 1809.09
   533.8 1806.42     540  1806.5   547.2 1808.97   551.6 1809.52   632.6 1809.99
   747.3 1809.78   759.6  1810.6   810.8 1810.85   857.4 1810.34   958.8 1812.09
  1173.6 1811.77  1242.4 1810.27  1307.3 1810.48  1325.9 1809.63  1356.5 1810.08
  1388.8  1809.3  1802.3 1810.32  1874.8 1812.21  1919.7 1816.56  1959.3 1822.61
#Mann= 3 ,-1 , 0
       0    .035       0   527.5    .045       0   547.2    .035       0
#XS Ineff= 2 , 0
                          996.61         1813.31
Permanent Ineff=
       F       F
Bank Sta=527.5,547.2
XS Rating Curve= 0 ,0
Exp/Cntr(USF)=0,0
Exp/Cntr=0.3,0.1

Type RM Length L Ch R = 1 ,1286    ,811.1,860.1,811.4
XS GIS Cut Line= 4
     2042444.355      154345.192     2042470.397      154798.317
     2043044.833      155698.202     2043564.147      155782.692
#Sta/Elev= 30
       0 1814.77    21.6 1812.55    44.6 1811.55      61 1812.08   225.3 1810.86
   284.5 1811.19   412.6 1809.56   466.4 1809.89   533.5  1807.8     562 1808.36
   588.4 1806.69   646.4 1807.61   705.7 1806.54   752.1 1807.12   797.71806.798
   809.8 1806.11   817.6 1804.45  826.651806.909   856.7 1808.13   899.4 1808.14
   930.5 1808.87  1127.4 1808.05  1214.6 1808.45  1241.5 1807.84  1319.9 1808.31
  1432.6 1807.98  1455.3  1808.7  1481.4 1807.97  1587.9 1809.16  2047.6  1810.2
#Mann= 3 ,-1 , 0
       0    .035       0   797.7    .045       0  826.65    .035       0
#XS Ineff= 2 , 0
          558.22 1810.16  946.86          1811.4
Permanent Ineff=
       F       F
Bank Sta=797.7,826.65
XS Rating Curve= 0 ,0
Exp/Cntr=0.3,0.1

Type RM Length L Ch R = 1 ,426     ,227.8,277.9,274.7
XS GIS Cut Line= 4
     2042236.673      154447.768     2042163.694      154984.628
2042311.24841785 155229.60613051      2042803.73      155886.859
#Sta/Elev= 30
       0 1811.75    37.4 1810.72   242.7 1809.15   355.3 1807.26   479.9 1806.29
   544.4 1806.65   573.4 1803.31     598 1802.76   617.1 1803.38   710.6 1802.84
   728.2 1804.13   731.61803.724   739.7 1801.69   754.51803.694   812.5 1804.65
   852.5  1806.7   859.6 1806.34     869 1803.86     877 1803.44   922.1 1804.69
   984.1 1803.48  1033.3 1804.65    1123 1804.02    1265 1805.68  1315.6 1804.53
  1336.1 1804.97  1351.7 1806.16  1385.3 1805.55  1629.7 1807.23  1649.1 1807.96
#Mann= 3 ,-1 , 0
       0    .035       0   731.6    .045       0   754.5    .035       0
#XS Ineff= 1 ,-1
   853.7    1648 1807.94
Permanent Ineff=
       F
Bank Sta=731.6,754.5
XS Rating Curve= 0 ,0
Exp/Cntr=0.3,0.1

Type RM Length L Ch R = 1 ,148     ,163.4,148.2,132.5
XS GIS Cut Line= 4
     2042112.975      154612.698     2042071.742      155177.224
     2042466.708      155700.227     2042730.814      155907.692
#Sta/Elev= 30
       0 1809.74     181 1806.65     316 1805.97   371.8 1803.48     431  1803.4
   457.9 1803.98   470.5 1803.47  478.781800.966   483.7 1799.62     487 1799.44
   499.91800.976   526.4 1803.15   590.6 1803.97   685.1 1803.32   713.9 1804.49
   796.8  1804.9   815.6 1803.46   881.2  1804.6   948.2 1804.31  1091.8 1805.78
  1122.4 1805.71  1136.5  1804.9  1162.5 1806.05  1216.1 1804.55  1304.9 1806.03
  1384.4  1805.7  1435.8 1806.72  1451.6 1805.71  1464.2  1806.9  1557.3 1807.28
#Mann= 3 ,-1 , 0
       0    .035       0  478.78    .045       0   499.9    .035       0
#XS Ineff= 2 , 0
                           790.5          1806.7
Permanent Ineff=
       F       F
Bank Sta=478.78,499.9
XS Rating Curve= 0 ,0
Exp/Cntr=0.3,0.1
LCMann Table=0

Chan Stop Cuts=-1
Use User Specified Reach Order=0
Composite Channel Slope=5